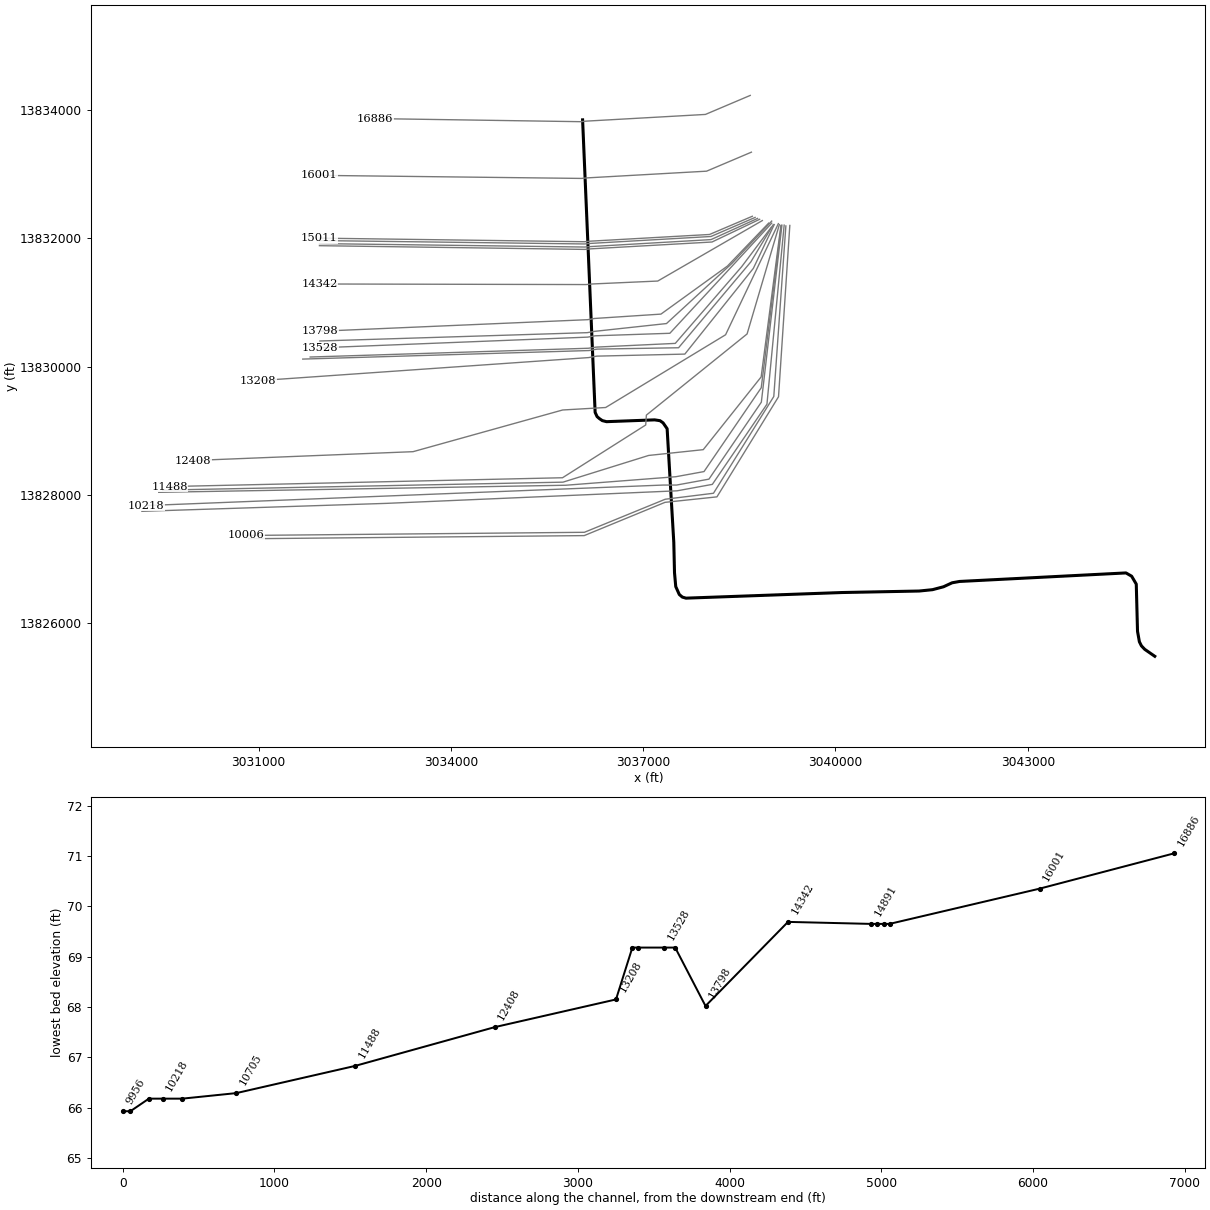
--- D129-00-00.prj (project) ---

Proj Title=D129-00-00
Current Plan=p01
Default Exp/Contr=.3,.1
English Units
Geom File=g02
Flow File=f04
Flow File=f05
Flow File=f02
Plan File=p01
Plan File=p06
Plan File=p05
Y Axis Title=Elevation
X Axis Title(PF)=Main Channel Distance
X Axis Title(XS)=Station
BEGIN DESCRIPTION:
Brays Bayou Watershed
Tributary 26.20
HCFCD Unit D129-00-00
Flood Hazard & Floodway Model
10, 2, 1, 0.2% Event
Filename D129.prj
Prepared by: Dodson & Associates, Inc.   Date: December 2003
Reviewed by:____________________	 Date:_________
STATUS (Final RAS, SVSQ)
FOR FLOOD HARZARD RECOVERY DATA ONLY,03/02/2004
Will Be Voided Upon Release of The Preliminary DFIRM
END DESCRIPTION:
DSS File=dss
DSS Export Rating Curves= 0
DSS Export Rating Curve Sorted= 0
DSS Export Volume Flow Curves= 0
DXF OffsetX= 0
DXF OffsetY= 0
DXF ScaleX= 1
DXF ScaleY= 10

--- D129-00-00.p01 (plan) ---

Plan Title=FEMA Effective June 2007
Version=Version 3.0.1  Mar 2001
Short Identifier=FEMAeff0607
Geom File=g02
Flow File=f04
Subcritical Flow
K Sum by GR= 0
Std Step Tol= 0.01
Critical Tol= 0.01
Num of Std Step Trials= 20
Max Error Tol= 0.3
Flow Tol Ratio= 0.001
Split Flow NTrial= 30
Split Flow Tol= 0.02
Split Flow Ratio= 0.02
Log Output Level= 0
Friction Slope Method= 1
Unsteady Friction Slope Method= 2
Parabolic Critical Depth
Global Vel Dist= 0 , 0 , 0
Global Log Level= 0
CheckData=True
Encroach Param=-1 ,0,0, 0
Computation Interval=1HOUR
Output Interval=1HOUR
Run HTab= 0
Run UNet= 0
Run PostProcess= 0
UNET Theta= 1
UNET ZTol= 0.02
UNET ZSATol= 0.1
UNET MxIter= 20
UNET MaxInSteps= 20
UNET DtIC= 0
UNET DtMin= 0
UNET MaxCRTS= 20
UNET WFStab= 2
UNET SFStab= 1
UNET WFX= 1
UNET SFX= 1
UNET Convert EG Bridges=-1
UNET Use Existing IB Tables=-1
Instantaneous Interval=1HOUR
Write IC File= 0
Write Velocity= 0
Write Detailed= 0

--- D129-00-00.p05 (plan) ---

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Plan Title=Storage Routing
Short Identifier=Store_Rout
Geom File=g02
Flow File=f02

--- D129-00-00.p06 (plan) ---

Plan Title=Floodway
Version=Version 3.0.1  Mar 2001
Short Identifier=Floodway0607
Geom File=g02
Flow File=f05
Subcritical Flow
K Sum by GR= 0
Std Step Tol= 0.01
Critical Tol= 0.01
Num of Std Step Trials= 20
Max Error Tol= 0.3
Flow Tol Ratio= 0.001
Split Flow NTrial= 30
Split Flow Tol= 0.02
Split Flow Ratio= 0.02
Log Output Level= 0
Friction Slope Method= 1
Unsteady Friction Slope Method= 2
Parabolic Critical Depth
Global Vel Dist= 0 , 0 , 0
Global Log Level= 0
CheckData=True
Encroach Param=-1 ,0,0, 2
Encroach River=D129-00-00
Encroach Reach=Reach 0
Encroach Node=16886
       1 2618.41 2720.03
Encroach Node=16001
       1 2606.16 2707.73
Encroach Node=15011
       1 2601.54 2670.03
Encroach Node=14976
       1 2646.54 2715.03
Encroach Node=14952
       1 2646.54 2758.03
Encroach Node=14927
       1 2689.54 2758.03
Encroach Node=14891
       1 2707.84 2817.99
Encroach Node=14342
       1 2908.28 2990.42
Encroach Node=13798
       1 3264.91 3343.29
Encroach Node=13598
       1 3416.42 3522.98
Encroach Node=13528
       1 3526.26 3602.42
Encroach Node=13440
       1 3526.26 3690.88
Encroach Node=13351
       1 3617.26 3690.88
Encroach Node=13316
       1 3735.37 3815.88
Encroach Node=13208
       1 3863.46 3952.47
Encroach Node=12408
       1 4212.98 4321.04
Encroach Node=11488
       1 3831.66 3934.36
Encroach Node=10705
       1 4264.62 4421.26
Encroach Node=10349
       1  4551.5 4751.74
Encroach Node=10218
       1 4744.36 4903.88
Encroach Node=10173
       1 4744.36 5042.88
Encroach Node=10128
       1  4881.7 5042.88
Encroach Node=10006
       1  5067.2  5170.2
Encroach Node=9956
       1 5179.15 5285.32
Encroach Node=9532
       1 5654.69 5776.67
Encroach Node=8554
       1 6351.54 6465.18
Encroach Node=7459
       1 4393.58 4530.65
Encroach Node=6333
       1 4043.93 4202.84
Encroach Node=6184
       1 4063.13 4210.84
Encroach Node=6053
       1 4035.34 4186.38
Encroach Node=5999
       1 4035.34  4244.7
Encroach Node=5945
       1 4075.57  4244.7
Encroach Node=5817
       1 4080.13 4232.44
Encroach Node=5291
       1 6293.29 6428.88
Encroach Node=4906
       1 6333.97 6450.13
Encroach Node=4805
       1 7664.97 7782.37
Encroach Node=4784
       1 7664.97 8049.41
Encroach Node=4762
       1 7949.97 8049.41
Encroach Node=4664
       1 7899.97 7999.41
Encroach Node=4339
       1 7738.96 7883.46
Encroach Node=3578
       1 6805.52 6936.91
Encroach Node=2731
       1 6787.94 6925.27
Encroach Node=2652
       1 6789.94 6927.27
Encroach Node=2618
       1 6789.94 6927.27
Encroach Node=2615
       1 6789.94 6927.27
Encroach Node=2515
       1 6773.92 6922.27
Encroach Node=1175
       1  885.04  987.37
Encroach Node=467
       1  986.48 1136.03
Encroach Reach=D129-00-00_0005
Encroach Node=16886
       1 2618.41 2720.03
Encroach Node=16001
       1 2606.16 2707.73
Encroach Node=15011
       1 2601.54 2670.03
Encroach Node=14976
       1 2646.54 2715.03
Encroach Node=14952
       1 2646.54 2758.03
Encroach Node=14927
       1 2689.54 2758.03
Encroach Node=14891
       1 2707.84 2817.99
Encroach Node=14342
       1 2908.28 2990.42
Encroach Node=13798
       1 3264.91 3343.29
Encroach Node=13598
       1 3416.42 3522.98
Encroach Node=13528
       1 3526.26 3602.42
Encroach Node=13440
       1 3526.26 3690.88
Encroach Node=13351
       1 3617.26 3690.88
Encroach Node=13316
       1 3735.37 3815.88
Encroach Node=13208
       1 3863.46 3952.47
Encroach Node=12408
       1 4212.98 4321.04
Encroach Node=11488
       1 3831.66 3934.36
Encroach Node=10705
       1 4264.62 4421.26
Encroach Node=10349
       1  4551.5 4751.74
Encroach Node=10218
       1 4744.36 4903.88
Encroach Node=10173
       1 4744.36 5042.88
Encroach Node=10128
       1  4881.7 5042.88
Encroach Node=10006
       1  5067.2  5170.2
Encroach Node=9956
       1 5179.15 5285.32
Encroach Node=9532
       1 5654.69 5776.67
Encroach Node=8554
       1 6351.54 6465.18
Encroach Node=7459
       1 4393.58 4530.65
Encroach Node=6333
       1 4043.93 4202.84
Encroach Node=6184
       1 4063.13 4210.84
Encroach Node=6053
       1 4035.34 4186.38
Encroach Node=5999
       1 4035.34  4244.7
Encroach Node=5945
       1 4075.57  4244.7
Encroach Node=5817
       1 4080.13 4232.44
Encroach Node=5291
       1 6293.29 6428.88
Encroach Node=4906
       1 6333.97 6450.13
Encroach Node=4805
       1 7664.97 7782.37
Encroach Node=4784
       1 7664.97 8049.41
Encroach Node=4762
       1 7949.97 8049.41
Encroach Node=4664
       1 7899.97 7999.41
Encroach Node=4339
       1 7738.96 7883.46
Encroach Node=3578
       1 6805.52 6936.91
Encroach Node=2731
       1 6787.94 6925.27
Encroach Node=2652
       1 6789.94 6927.27
Encroach Node=2618
       1 6789.94 6927.27
Encroach Node=2615
       1 6789.94 6927.27
Encroach Node=2515
       1 6773.92 6922.27
Encroach Node=1175
       1  885.04  987.37
Encroach Node=467
       1  986.48 1136.03
Computation Interval=1HOUR
Output Interval=1HOUR
Run HTab= 0
Run UNet= 0
Run PostProcess= 0
UNET Theta= 1
UNET ZTol= 0.02
UNET ZSATol= 0.1
UNET MxIter= 20
UNET MaxInSteps= 20
UNET DtIC= 0
UNET DtMin= 0
UNET MaxCRTS= 20
UNET WFStab= 2
UNET SFStab= 1
UNET WFX= 1
UNET SFX= 1
UNET Convert EG Bridges=-1
UNET Use Existing IB Tables=-1
Instantaneous Interval=1HOUR
Write IC File= 0
Write Velocity= 0
Write Detailed= 0

--- D129-00-00.f04 (steady flow) ---

Flow Title=FEMA Effective June 2007
Version=Version 3.0.1  Mar 2001
Number of Profiles= 4
Profile Names=10PCT_10yr,2PCT_50yr,1PCT_100yr,0.2PCT_500yr
River Rch & RM=D129-00-00,D129-00-00_0005 ,16886
     330     530     764    1704
River Rch & RM=D129-00-00,D129-00-00_0005 ,15011
     330     530     764    1704
River Rch & RM=D129-00-00,D129-00-00_0005 ,14342
     404     642     900    1887
River Rch & RM=D129-00-00,D129-00-00_0005 ,13208
     550     859    1154    2202
River Rch & RM=D129-00-00,D129-00-00_0005 ,11488
     723    1113    1439    2526
River Rch & RM=D129-00-00,D129-00-00_0005 ,9956
     929    1412    1762    2865
River Rch & RM=D129-00-00,D129-00-00_0005 ,8554
    1130    1699    2063    3160
River Rch & RM=D129-00-00,D129-00-00_0005 ,7459
    1515    2244    2614    3662
River Rch & RM=D129-00-00,D129-00-00_0005 ,5817
    1691    2491    2857    3865
River Rch & RM=D129-00-00,D129-00-00_0005 ,4339
    1937    2833    3187    4130
River Rch & RM=D129-00-00,D129-00-00_0005 ,2515
    2140    3114    3454    4337
River Rch & RM=D129-00-00,D129-00-00_0005 ,1175
    2335    3383    3707    4527
Boundary for River Rch & Prof#=D129-00-00,D129-00-00_0005 , 1
Up Type= 0
Dn Type= 3
Dn Slope=.001
Boundary for River Rch & Prof#=D129-00-00,D129-00-00_0005 , 2
Up Type= 0
Dn Type= 3
Dn Slope=.001
Boundary for River Rch & Prof#=D129-00-00,D129-00-00_0005 , 3
Up Type= 0
Dn Type= 3
Dn Slope=.001
Boundary for River Rch & Prof#=D129-00-00,D129-00-00_0005 , 4
Up Type= 0
Dn Type= 3
Dn Slope=.001
DSS Import GetInterval= 0
DSS Import GetPeak= 0
DSS Import FillOption= 0

--- D129-00-00.f02 (steady flow) ---

Flow Title=Storage Routing
Version=Version 3.0.1  Mar 2001
Number of Profiles= 8
Profile Names=0.1,0.2,0.4,0.6,0.8,1.0,1.2,1.5
River Rch & RM=D129-00-00,D129-00-00_0005 ,16886
     261     522    1044    1566    2088    2610    3132    3915
River Rch & RM=D129-00-00,D129-00-00_0005 ,5817
     371     742    1484    2226    2968    3710    4452    5565
Boundary for River Rch & Prof#=D129-00-00,D129-00-00_0005 , 1
Up Type= 0
Dn Type= 3
Dn Slope=.001
Boundary for River Rch & Prof#=D129-00-00,D129-00-00_0005 , 2
Up Type= 0
Dn Type= 3
Dn Slope=.001
Boundary for River Rch & Prof#=D129-00-00,D129-00-00_0005 , 3
Up Type= 0
Dn Type= 3
Dn Slope=.001
Boundary for River Rch & Prof#=D129-00-00,D129-00-00_0005 , 4
Up Type= 0
Dn Type= 3
Dn Slope=.001
Boundary for River Rch & Prof#=D129-00-00,D129-00-00_0005 , 5
Up Type= 0
Dn Type= 3
Dn Slope=.001
Boundary for River Rch & Prof#=D129-00-00,D129-00-00_0005 , 6
Up Type= 0
Dn Type= 3
Dn Slope=.001
Boundary for River Rch & Prof#=D129-00-00,D129-00-00_0005 , 7
Up Type= 0
Dn Type= 3
Dn Slope=.001
Boundary for River Rch & Prof#=D129-00-00,D129-00-00_0005 , 8
Up Type= 0
Dn Type= 3
Dn Slope=.001
DSS Import GetInterval= 0
DSS Import GetPeak= 0
DSS Import FillOption= 0

--- D129-00-00.f05 (steady flow) ---

Flow Title=Floodway
Version=Version 3.0.1  Mar 2001
Number of Profiles= 2
Profile Names=1PCT_100yr,1PCTFloodway_100yrFW
River Rch & RM=D129-00-00,D129-00-00_0005 ,16886
     764     764
River Rch & RM=D129-00-00,D129-00-00_0005 ,14342
     900     900
River Rch & RM=D129-00-00,D129-00-00_0005 ,13208
    1154    1154
River Rch & RM=D129-00-00,D129-00-00_0005 ,11488
    1439    1439
River Rch & RM=D129-00-00,D129-00-00_0005 ,9956
    1762    1762
River Rch & RM=D129-00-00,D129-00-00_0005 ,8554
    2063    2063
River Rch & RM=D129-00-00,D129-00-00_0005 ,7459
    2614    2614
River Rch & RM=D129-00-00,D129-00-00_0005 ,5817
    2857    2857
River Rch & RM=D129-00-00,D129-00-00_0005 ,4339
    3187    3187
River Rch & RM=D129-00-00,D129-00-00_0005 ,2515
    3454    3454
River Rch & RM=D129-00-00,D129-00-00_0005 ,1175
    3707    3707
Boundary for River Rch & Prof#=D129-00-00,D129-00-00_0005 , 1
Up Type= 0
Dn Type= 1
Dn Known WS=75.01
Boundary for River Rch & Prof#=D129-00-00,D129-00-00_0005 , 2
Up Type= 0
Dn Type= 1
Dn Known WS=75.01
DSS Import GetInterval= 0
DSS Import GetPeak= 0
DSS Import FillOption= 0

--- D129-00-00.g02 (geometry) ---

Geom Title=D129-00-00 June 2007
Version=Version 3.0.1  Mar 2001

River Reach=D129-00-00      ,D129-00-00_0005
Reach XY= 30
      3036054.77    13833851.859     3036250.388    13829284.397
      3036280.83    13829218.392     3036318.255    13829186.107
     3036362.719    13829155.684     3036428.245    13829139.303
     3037179.456    13829167.385      3037262.72    13829154.597
     3037310.509    13829120.581     3037373.695    13829029.312
     3037477.682    13827253.225     3037488.777    13826781.695
     3037508.193     13826563.96     3037563.667     13826440.53
      3037610.82    13826400.312     3037667.681    13826383.669
     3040100.053     13826471.45     3041305.267    13826494.852
     3041513.547    13826515.914     3041685.387    13826561.186
     3041820.116    13826623.564     3041936.407    13826644.397
     3044532.591    13826777.535     3044621.349    13826726.221
     3044693.466    13826602.792     3044712.881    13825866.374
     3044742.005    13825702.726     3044773.903    13825638.931
     3044825.216    13825584.843     3044982.118    13825475.922

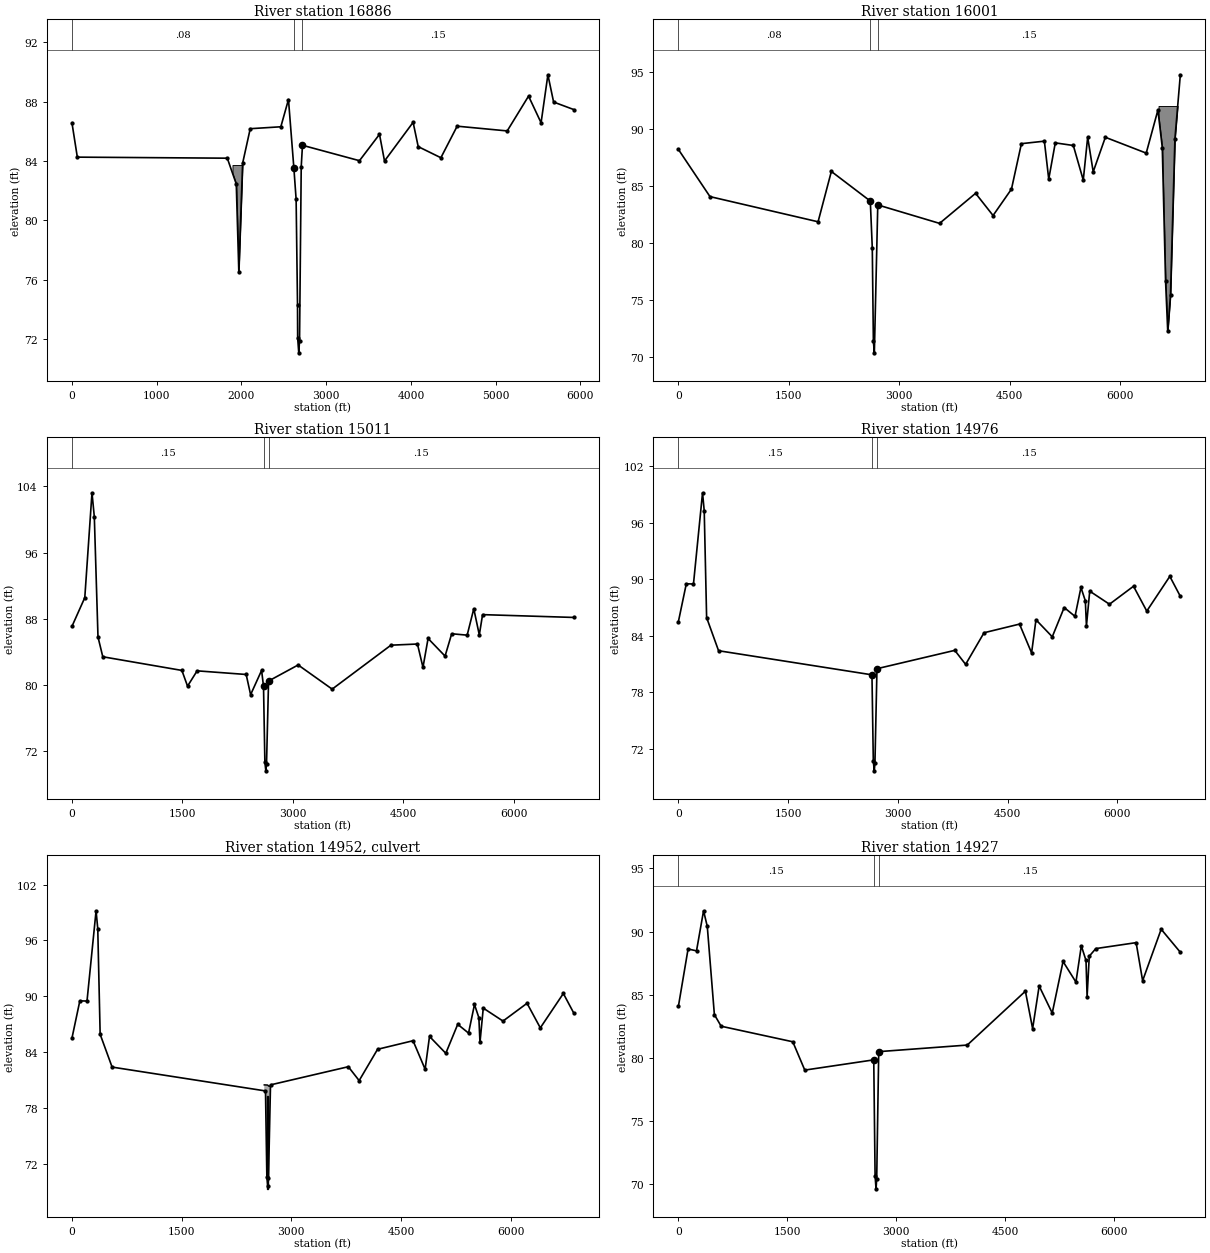
Type RM Length L Ch R = 1 ,16886   ,888.89,885.41,900.2
BEGIN DESCRIPTION:
Additional Cross Section to Meet LODS
END DESCRIPTION:
XS GIS Cut Line= 6
      3038670.32    13834233.381     3037971.009    13833936.486
      3036121.25     13833832.49     3036081.989     13833829.03
     3036017.422     13833823.39     3032812.555    13833871.718
#Sta/Elev= 30
       0   86.58   63.46   84.26 1832.85   84.19 1938.75   82.45  1968.8   76.54
 2013.87   83.85 2103.47   86.18 2464.58   86.31 2554.72   88.15 2618.41   83.52
 2644.94   81.42 2661.37    74.3 2663.08   72.06 2676.22   71.05 2685.27   71.86
 2705.17   83.62 2720.03   85.06 3392.23   84.02 3628.69    85.8 3687.81      84
 4025.36   86.61 4085.37   84.97 4352.85   84.22 4544.98   86.35 5135.49   86.03
 5387.37   88.38 5535.16   86.58 5615.54   89.82 5682.95   87.98 5921.86   87.47
#Mann= 3 , 0 , 0
       0     .08       0 2618.41     .04       0 2720.03     .15       0
#XS Ineff= 2 , 0
       0 2569.54          2735.1       0
Permanent Ineff=
       T       T
#Block Obstruct= 1 ,-1
 1894.04 2026.49   83.73
Bank Sta=2618.41,2720.03
XS Rating Curve= 0
Exp/Cntr=.3,.1

Type RM Length L Ch R = 1 ,16001   ,995.63,989.61,1014.6
BEGIN DESCRIPTION:
Additional Cross Section to Meet LODS
END DESCRIPTION:
XS GIS Cut Line= 6
      3038688.53     13833347.42     3037989.226    13833050.525
     3036139.467    13832946.529     3036100.206    13832943.069
     3036035.639    13832937.429      3031935.67    13832985.216
#Sta/Elev= 30
       0   88.21  428.79   84.07  1896.9   81.86 2077.19   86.28 2606.16   83.68
 2633.11   79.57 2648.08   71.36 2661.22   70.35 2707.73   83.34  3546.9   81.72
 4036.23   84.36 4273.48   82.41 4523.55   84.73 4658.56   88.72  4970.4   88.94
 5029.72   85.61 5118.69   88.79 5363.61   88.56 5498.62   85.52 5558.62   89.29
 5633.63   86.25 5798.64   89.28 6353.68   87.89 6512.54   91.67 6571.85   88.38
 6616.33   76.66 6645.99   72.25  6683.7   75.46  6743.7   89.15 6816.88   94.77
#Mann= 3 , 0 , 0
       0     .08       0 2606.16     .04       0 2707.73     .15       0
#XS Ineff= 2 , 0
       0  2588.3         2750.55       0
Permanent Ineff=
       T       T
#Block Obstruct= 1 ,-1
 6520.97 6783.66   92.03
Bank Sta=2606.16,2707.73
XS Rating Curve= 0
Exp/Cntr=.3,.1

Type RM Length L Ch R = 1 ,15011   ,35.9,35.03,35.23
BEGIN DESCRIPTION:
15011.22--u/s approach Piping Rock culvert;  channel copied from 14927
END DESCRIPTION:
XS GIS Cut Line= 6
      3038702.93    13832346.492     3038034.949    13832062.176
      3036185.19     13831958.18     3036145.929     13831954.72
     3036081.362     13831949.08     3031948.687    13832004.899
#Sta/Elev= 30
       0    87.1  174.36   90.57  272.17  103.24  303.83  100.33  353.68   85.82
  418.74   83.43 1493.01   81.78 1569.75   79.88 1699.95   81.73 2366.01   81.29
  2426.1   78.85 2575.48   81.78 2601.54   79.85 2620.08   70.66 2633.22   69.65
 2642.27   70.46 2670.03    80.5 3071.78   82.44 3533.75   79.52 4331.89   84.83
 4691.92   84.97 4766.93   82.15 4836.28   85.64 5066.96   83.51 5156.97   86.21
 5366.98   86.04 5456.99   89.23 5531.94   86.07 5576.35   88.52 6815.93   88.18
#Mann= 3 , 0 , 0
       0     .15       0 2601.54     .04       0 2670.03     .15       0
#XS Ineff= 2 , 0
       0    2415            2706       0
Permanent Ineff=
       T       T
Bank Sta=2601.54,2670.03
XS Rating Curve= 0
Exp/Cntr=.5,.3

Type RM Length L Ch R = 1 ,14976   ,51.07,48.81,48.08
BEGIN DESCRIPTION:
14976.19--u/s face Piping Rock culvert; channel copied from 14927
END DESCRIPTION:
XS GIS Cut Line= 6
     3038746.474    13832328.356      3038057.45    13832030.607
     3036187.707     13831923.26     3036148.807     13831919.84
     3036082.672     13831914.06     3031948.842    13831967.161
#Sta/Elev= 30
       0   85.51  107.82   89.52  205.86    89.5  329.88   99.19  352.93   97.27
  385.61   85.93  549.02   82.41 2646.54   79.85 2665.08   70.66 2678.22   69.65
 2687.27   70.46 2715.03    80.5 3779.07   82.45 3927.18   80.96 4178.97   84.32
 4664.19   85.24 4829.21   82.18 4889.21    85.7 5112.06   83.89 5274.98      87
 5423.09   86.06 5504.26   89.13 5564.27   87.71 5579.27   85.05 5624.27   88.74
 5894.29   87.35 6222.88   89.26 6404.34   86.62 6719.36   90.31 6863.03   88.19
#Mann= 3 , 0 , 0
       0     .15       0 2646.54     .04       0 2715.03     .15       0
#XS Ineff= 2 , 0
       0    2462            2750       0
Permanent Ineff=
       T       T
Bank Sta=2646.54,2715.03
XS Rating Curve= 0
Exp/Cntr=.5,.3

Type RM Length L Ch R = 2 ,14952   ,,,
BEGIN DESCRIPTION:
Piping Rock Culvert
END DESCRIPTION:
Bridge Culvert--1,0,-1,-1, 0
Deck Dist Width WeirC Skew NumUp NumDn MinLoCord MaxHiCord MaxSubmerge Is_Ogee
5,40,2.6,0, 5, 5, , , .95, 0, 0,0,,
    2630 2659.63 2676.13 2692.73 2715.03
    80.5   80.49   80.48   80.36   80.37
                                        
    2674 2702.63 2719.13 2735.73 2758.03
    80.5   80.49   80.48   80.36   80.37
                                        
BR Coef=-1 , 0 , 0 ,, 0 ,,,.8,-1,,0,
WSPro=,,,, 1 ,,,, 0 ,,,, 0 ,,,,-1 ,-1 ,-1 , 0 , 0 , 0 , 0 , 0
Culvert=2,10,12.5,40,.013,.5,1,8,1,69.34,2676.18,69.34,2719.18,Culvert #1  , 0 ,5
Culvert Bottom n=.013
BC Design=,, 0 ,, 0 ,,,,,,

Type RM Length L Ch R = 1 ,14927   ,37.16,36.26,36.97
BEGIN DESCRIPTION:
14927.38--d/s face Piping Rock culvert; surveyed channel
END DESCRIPTION:
XS GIS Cut Line= 5
      3038784.32    13832312.593     3038058.402    13831982.219
      3036191.27    13831873.841     3036084.395      13831866.1
     3031949.036    13831919.698
#Sta/Elev= 30
       0   84.09     133   88.62  249.21   88.47  346.26   91.64  397.53    90.4
  495.12   83.43  588.23   82.51 1574.77   81.28 1739.94   79.04 2689.54   79.85
 2708.08   70.66 2721.22   69.65 2730.27   70.46 2758.03    80.5 3976.99   81.02
  4777.5   85.28 4877.06   82.32 4967.07   85.69 5147.09   83.55 5295.83   87.63
 5473.54      86 5547.59   88.87 5612.12   87.71 5627.13   84.86 5657.13   88.05
 5747.14   88.65 6302.18   89.12 6391.72   86.11 6647.21   90.18  6910.7   88.36
#Mann= 3 , 0 , 0
       0     .15       0 2689.54     .04       0 2758.03     .15       0
#XS Ineff= 2 , 0
       0    2510            2793       0
Permanent Ineff=
       T       T
Bank Sta=2689.54,2758.03
XS Rating Curve= 0
Exp/Cntr=.5,.3

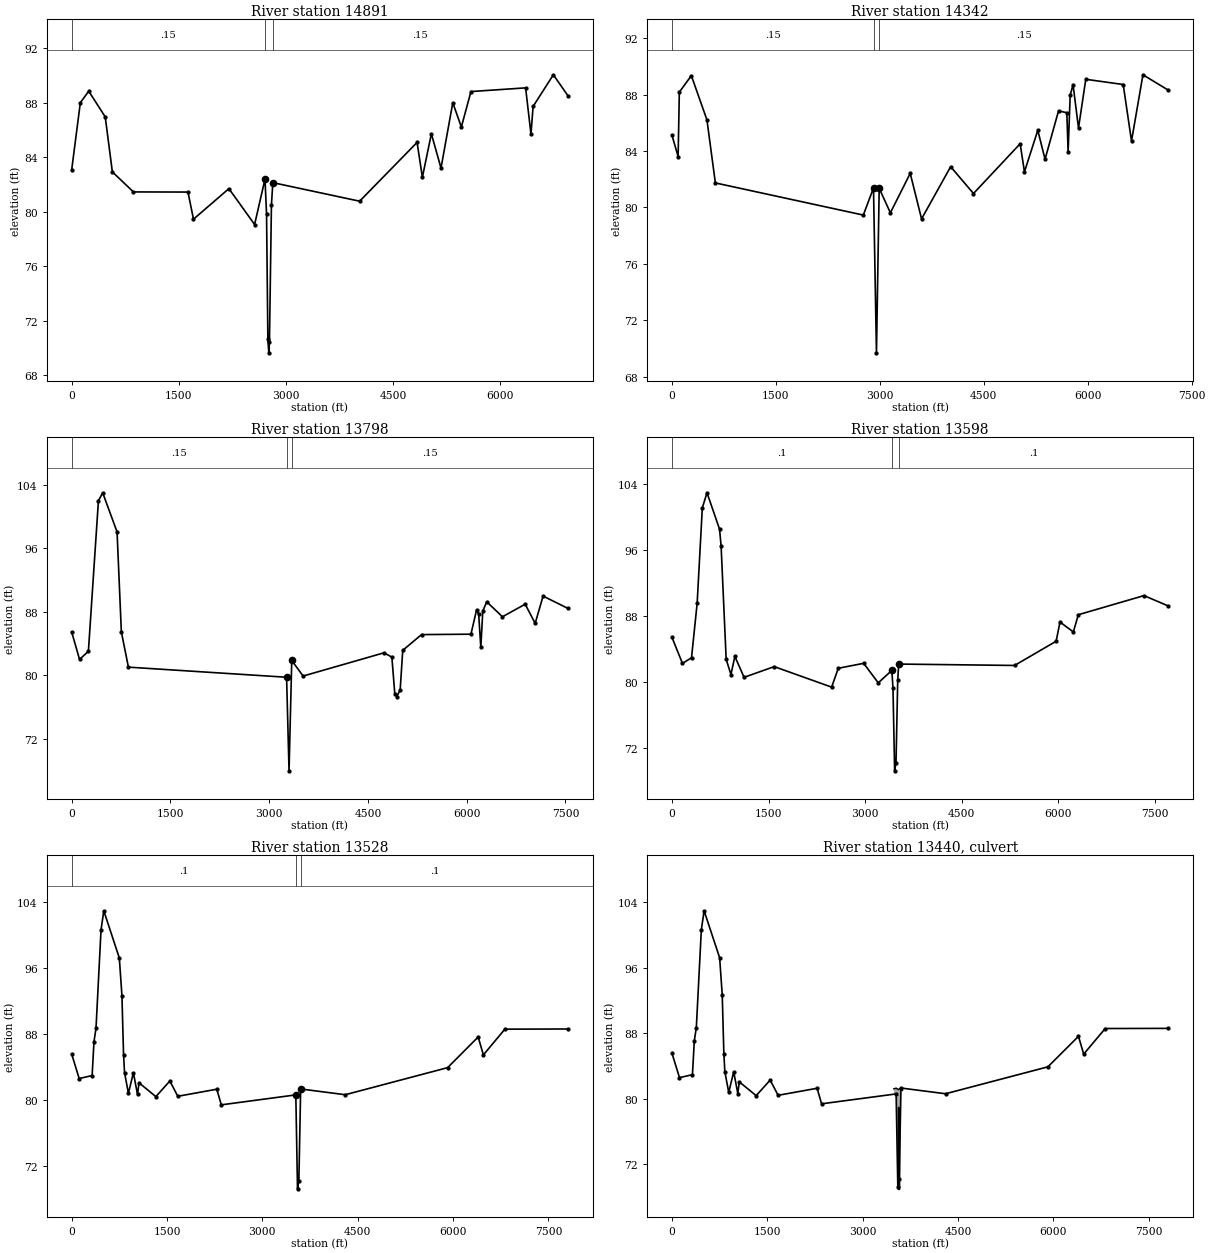
Type RM Length L Ch R = 1 ,14891   ,574.12,549.07,555.63
BEGIN DESCRIPTION:
14891.12--d/s exit Piping Rock culvert; channel copied from 14927
END DESCRIPTION:
XS GIS Cut Line= 6
     3038816.888    13832299.029     3038073.744    13831944.578
      3036193.82     13831838.47     3036155.795     13831835.12
     3036085.855     13831829.02     3031949.169    13831887.177
#Sta/Elev= 30
       0   83.06  121.19   87.99  239.06   88.84  470.19   86.95   569.9   82.92
  864.66   81.45  1629.2   81.44 1705.99   79.45 2202.42   81.69 2562.35   79.06
 2707.84   82.39 2729.54   79.85 2748.08   70.66 2761.22   69.65 2770.27   70.46
 2798.03    80.5 2817.99   82.13 4033.11   80.77 4838.23   85.08  4912.2   82.52
 5038.21   85.71 5173.23    83.2 5338.24   87.99 5458.26   86.21  5592.7   88.81
 6358.34   89.08 6433.35   85.69 6463.35   87.72 6746.59   90.04 6951.73    88.5
#Mann= 3 , 0 , 0
       0     .15       0 2707.84     .04       0 2817.99     .15       0
#XS Ineff= 2 , 0
       0    2550            2831       0
Permanent Ineff=
       T       T
Bank Sta=2707.84,2817.99
XS Rating Curve= 0
Exp/Cntr=.3,.1

Type RM Length L Ch R = 1 ,14342   ,547.12,543.88,565.24
BEGIN DESCRIPTION:
 14342.05--surveyed channel
END DESCRIPTION:
XS GIS Cut Line= 5
     3038859.253    13832279.512     3037227.407    13831334.978
     3036216.911    13831289.876     3036108.236    13831280.148
     3031951.615    13831289.057
#Sta/Elev= 30
       0   85.12   88.68   83.61  106.01   88.18  279.33   89.35  504.64   86.21
  625.96   81.74 2761.26   79.46 2908.28   81.38 2950.97   69.69 2990.42   81.36
 3151.83   79.62 3438.26   82.42 3601.84   79.19 4021.84   82.89 4351.31   80.99
 5024.86   84.52 5086.84   82.53 5279.32   85.47 5384.09   83.42 5578.68   86.85
 5698.42   86.72 5716.84   83.95 5746.84   87.96 5788.23   88.71 5866.84   85.63
 5971.84   89.09 6511.84   88.72 6631.84   84.71 6796.84   89.41 7162.73   88.32
#Mann= 3 , 0 , 0
       0     .15       0 2908.28     .04       0 2990.42     .15       0
#XS Ineff= 2 , 0
       0    2734            3022       0
Permanent Ineff=
       T       T
Bank Sta=2908.28,2990.42
XS Rating Curve= 0
Exp/Cntr=.3,.1

Type RM Length L Ch R = 1 ,13798   ,175.49,199.98,199.53
BEGIN DESCRIPTION:
 13798.16--surveyed channel
END DESCRIPTION:
XS GIS Cut Line= 6
      3038957.55    13832239.262     3038314.398    13831568.652
     3037277.255    13830818.716     3036241.784    13830750.715
     3036132.487    13830731.715     3031954.634    13830551.173
#Sta/Elev= 30
       0   85.47   119.7   82.02  254.09   83.04  406.49  101.96  471.51  102.96
  689.54   98.04  754.86   85.47  862.02   81.05 3264.91   79.78 3301.98   68.02
 3343.29   81.89 3515.48   79.93 4744.03   82.85 4864.14   82.31 4909.18   77.65
 4939.21   77.33 4990.54   78.21  5029.3   83.16 5314.56   85.14 6065.26   85.19
 6151.76   88.27 6183.14   87.69  6215.4   83.52 6245.43    88.1 6305.49   89.26
 6544.06   87.38 6889.29   88.96 7041.17   86.55 7161.29   89.98  7539.5   88.43
#Mann= 3 , 0 , 0
       0     .15       0 3264.91     .04       0 3343.29     .15       0
#XS Ineff= 2 , 0
       0    3051            3376       0
Permanent Ineff=
       T       T
Bank Sta=3264.91,3343.29
XS Rating Curve= 0
Exp/Cntr=.3,.1

Type RM Length L Ch R = 1 ,13598   ,117.53,70.59,72.28
BEGIN DESCRIPTION:
13598.19--u/s approach Westheimer culvert; channel copied from 13351
END DESCRIPTION:
XS GIS Cut Line= 6
       3039005.3    13832271.095     3038384.553    13831610.558
     3037363.569     13830671.23     3036242.255     13830549.54
      3036126.44     13830529.12     3031955.256    13830398.984
#Sta/Elev= 30
       0   85.38  162.75   82.22  303.44    82.9  391.05   89.52  471.51  101.11
  544.38  102.93   739.1   98.51  763.42   96.46  842.02   82.72  916.03   80.87
  977.17   83.07 1119.85   80.53 1588.65   81.83 2480.95   79.34 2584.15   81.63
 2978.86   82.23 3205.18   79.86 3416.42   81.37 3434.26   79.22 3459.94   69.18
 3481.44   70.19 3507.88   80.17 3522.98   82.14 5323.11   81.97 5969.42   84.91
 6029.44   87.24 6237.05   86.04  6314.5   88.13 7335.08   90.45 7712.51   89.19
#Mann= 3 , 0 , 0
       0      .1       0 3416.42     .04       0 3522.98      .1       0
#XS Ineff= 2 , 0
       0    3212            3547       0
Permanent Ineff=
       T       T
Bank Sta=3416.42,3522.98
XS Rating Curve= 0
Exp/Cntr=.5,.3

Type RM Length L Ch R = 1 ,13528   ,170.41,176.52,171.86
BEGIN DESCRIPTION:
13527.60--u/s face Westheimer culvert;  channel copied from 13351
END DESCRIPTION:
XS GIS Cut Line= 6
       3039005.3    13832239.262     3038383.634    13831563.983
     3037416.094    13830519.378     3036252.134      13830480.2
     3036133.679     13830459.31     3031955.691    13830292.558
#Sta/Elev= 30
       0   85.57  117.93   82.59  321.82   82.95   351.1   87.07  382.98   88.71
  461.83  100.65  505.31  102.98  749.74   97.24  790.75   92.68  816.18    85.5
  831.53   83.32  892.69   80.79  971.04    83.3 1035.74   80.65 1059.33   82.07
 1324.22   80.39 1544.97   82.29 1669.56   80.43 2282.93   81.29 2353.84   79.39
 3526.26    80.6 3552.94   69.18 3574.44   70.19 3602.42   81.32 4303.51   80.62
 5914.02   83.91 6394.99   87.64 6476.92   85.46 6815.32   88.59 7807.93   88.61
#Mann= 3 , 0 , 0
       0      .1       0 3526.26     .04       0 3602.42      .1       0
#XS Ineff= 2 , 0
       0    3290            3683       0
Permanent Ineff=
       T       T
Bank Sta=3526.26,3602.42
XS Rating Curve= 0
Exp/Cntr=.5,.3

Type RM Length L Ch R = 2 ,13440   ,,,
BEGIN DESCRIPTION:
Westheimer Culvert
END DESCRIPTION:
Bridge Culvert--1,0,-1,-1, 0
Deck Dist Width WeirC Skew NumUp NumDn MinLoCord MaxHiCord MaxSubmerge Is_Ogee
23,130,2.6,0, 5, 5, , , .95, 0, 0,0,,
 3490.85 3527.52 3563.52 3599.52 3624.36
   81.23    81.3   81.13   81.29   81.03
                                        
 3580.85 3617.52 3653.52 3689.52 3714.36
   81.23    81.3   81.13   81.29   81.03
                                        
BR Coef=-1 , 0 , 0 ,, 0 ,,,.8,-1,,1,
WSPro=,,,, 1 ,,,, 0 ,,,, 0 ,,,,-1 ,-1 ,-1 , 0 , 0 , 0 , 0 , 0
Culvert=2,10,6.1,130,.013,.5,1,8,3,69,3552.92,69,3642.92,Culvert #2  , 0 ,23
Culvert Bottom n=.013
Culvert=2,10,12.4,130,.013,.5,1,8,3,69,3563.52,69,3653.52,Culvert #1  , 0 ,23
Culvert Bottom n=.013
Culvert=2,10,6.8,130,.013,.5,1,8,3,69,3574.47,69,3664.47,Culvert #3  , 0 ,23
Culvert Bottom n=.013
BC Design=,, 0 ,, 0 ,,,,,,

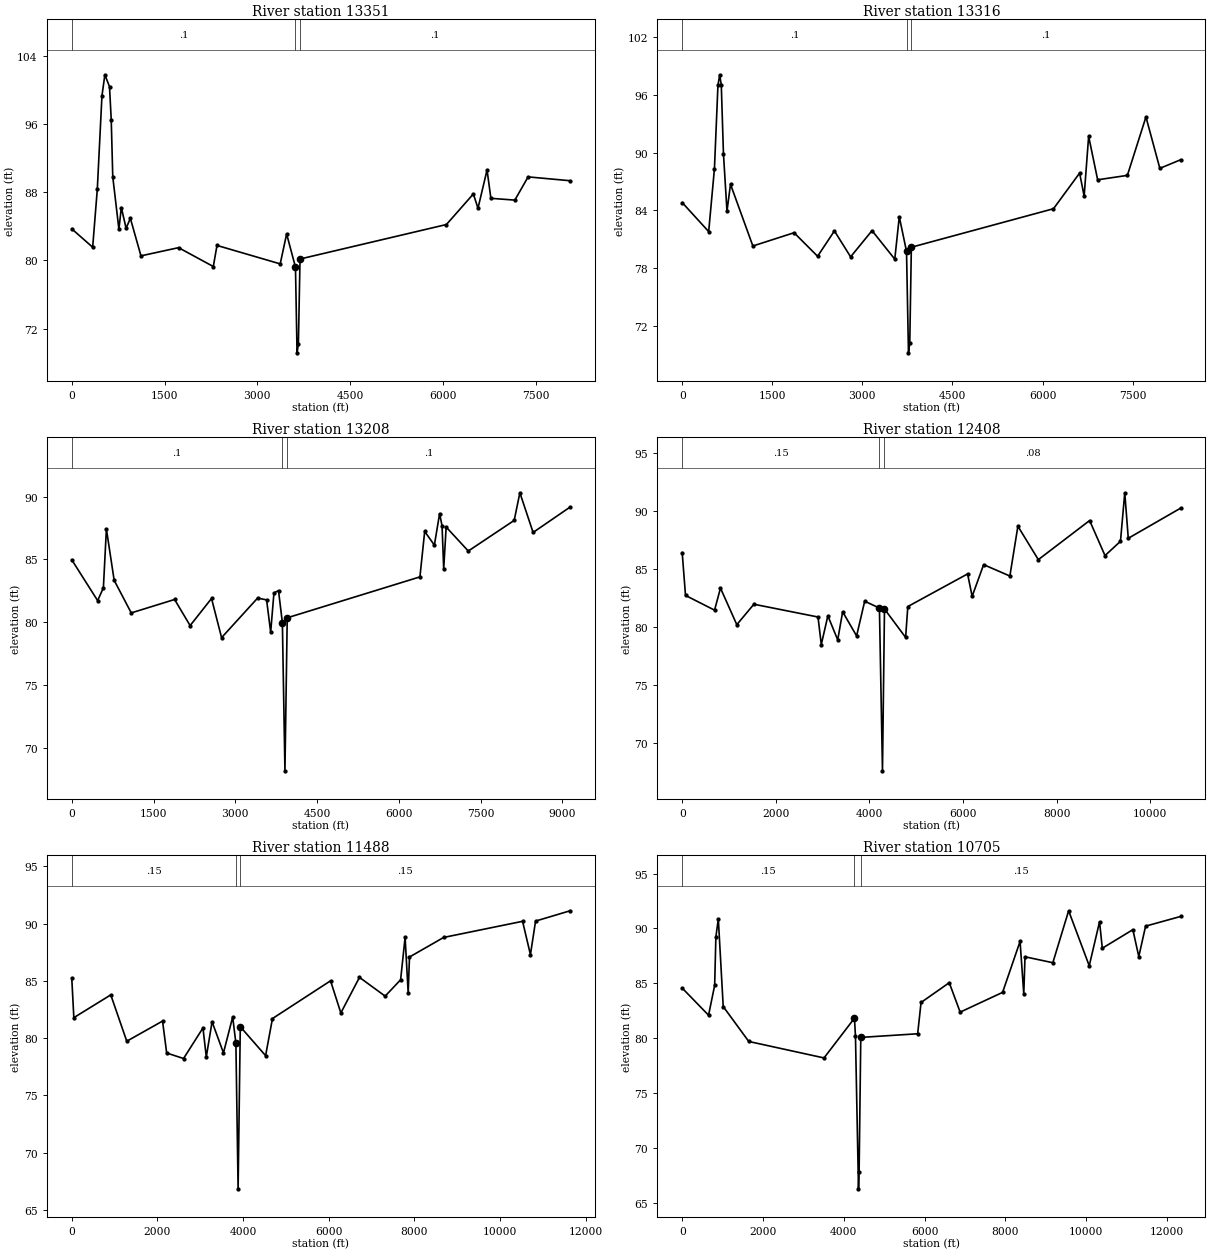
Type RM Length L Ch R = 1 ,13351   ,52.66,35.25,35.6
BEGIN DESCRIPTION:
13351.08--d/s face Westheimer culvert; surveyed channel
END DESCRIPTION:
XS GIS Cut Line= 6
     3039000.317    13832177.323      3038536.26    13831558.618
     3037500.948    13830361.578     3036266.911    13830303.455
     3036145.298    13830285.626     3031804.184    13830148.719
#Sta/Elev= 30
       0    83.7  338.01   81.55  413.01   88.36  488.01   99.28  535.14  101.75
  610.15  100.36     638    96.5     663   89.79   762.3   83.65  801.32    86.2
  878.51   83.77   947.3   84.94 1118.63   80.54 1726.92    81.5 2288.72   79.29
 2348.22   81.76 3370.62    79.6 3474.26   83.11 3617.26   79.22 3642.94   69.18
 3664.44   70.19 3690.88   80.17 6058.33   84.21 6493.55   87.79 6568.58   86.12
 6715.12    90.6  6777.1   87.28 7164.51   87.07 7378.99   89.79 8057.64   89.34
#Mann= 3 , 0 , 0
       0      .1       0 3617.26     .04       0 3690.88      .1       0
#XS Ineff= 2 , 0
       0    3430            3962       0
Permanent Ineff=
       T       T
Bank Sta=3617.26,3690.88
XS Rating Curve= 0
Exp/Cntr=.5,.3

Type RM Length L Ch R = 1 ,13316   ,108.51,107.98,119.95
BEGIN DESCRIPTION:
13315.83--d/s exit Westheimer culvert; channel copied from 13351
END DESCRIPTION:
XS GIS Cut Line= 6
     3039029.174    13832215.387     3038679.471    13831633.695
     3037552.211    13830293.515     3036281.774     13830272.18
     3036155.398     13830249.89      3031688.55    13830116.449
#Sta/Elev= 30
       0   84.82  440.92    81.8  536.98   88.35  595.21   97.01  624.32   98.12
  650.94   97.05  686.81   89.92  745.62   83.93  804.42   86.72 1176.83    80.3
 1862.85   81.68 2254.87   79.23 2534.67   81.87 2804.71   79.17 3161.02    81.9
 3539.81   78.93 3614.82   83.34 3735.37   79.74 3767.94   69.18 3789.44   70.19
 3815.88   80.17 6182.84   84.18 6618.03   87.89 6693.07   85.49  6768.1   91.72
 6918.02   87.19 7413.02   87.65  7722.4   93.73 7953.63   88.38 8297.73   89.27
#Mann= 3 , 0 , 0
       0      .1       0 3735.37     .04       0 3815.88      .1       0
#XS Ineff= 2 , 0
       0    3580            4110       0
Permanent Ineff=
       T       T
Bank Sta=3735.37,3815.88
XS Rating Curve= 0
Exp/Cntr=.3,.1

Type RM Length L Ch R = 1 ,13208   ,465.54,799.47,787.17
BEGIN DESCRIPTION:
 13207.85--surveyed channel
END DESCRIPTION:
XS GIS Cut Line= 6
     3039044.831    13832216.855     3038718.541    13831532.443
     3037649.954    13830194.296     3036276.771    13830162.653
     3036147.788    13830139.805     3030994.865     13829779.14
#Sta/Elev= 30
       0   84.96  474.49   81.71  580.02   82.73  635.19   87.41  777.66   83.33
 1091.05   80.73  1886.4    81.8 2171.18   79.72 2563.87   81.88 2748.17   78.76
 3408.56   81.91  3573.8   81.77 3648.82    79.2 3708.84   82.32  3792.5   82.51
 3863.46   79.95 3910.56   68.15 3952.47   80.34 6386.77    83.6 6474.12   87.22
 6651.98   86.13 6747.65   88.64 6792.76   87.67 6822.83   84.24 6867.94   87.57
 7273.93   85.66 8115.99    88.1 8220.31    90.3 8462.83   87.14 9141.12   89.16
#Mann= 3 , 0 , 0
       0      .1       0 3863.46     .04       0 3952.47      .1       0
#XS Ineff= 2 , 0
       0    3814            4315       0
Permanent Ineff=
       T       T
Bank Sta=3863.46,3952.47
XS Rating Curve= 0
Exp/Cntr=.3,.1

Type RM Length L Ch R = 1 ,12408   ,402.8,920.73,902.36
BEGIN DESCRIPTION:
 12408.38--surveyed channel
END DESCRIPTION:
XS GIS Cut Line= 6
     3039108.757    13832231.304     3038285.667    13830496.114
     3036414.355    13829360.421     3035743.263    13829321.704
     3033409.275    13828670.766     3029972.893    13828532.814
#Sta/Elev= 30
       0   86.39   70.62   82.71  691.25   81.44  817.71   83.34 1166.35   80.19
 1531.24   81.95 2900.96   80.85 2971.15   78.48 3111.52   80.95 3322.07   78.88
 3427.35    81.3 3725.64   79.22 3898.01   82.21 4212.98   81.62 4278.26    67.6
 4321.04   81.54 4772.83   79.09 4819.22   81.75 6096.16   84.56 6193.64   82.63
 6438.75   85.36 6999.36   84.38 7170.66   88.67 7607.25   85.79 8703.13   89.16
 9031.68   86.14 9361.91   87.37 9453.73   91.55 9528.79   87.63 10644.3   90.22
#Mann= 3 , 0 , 0
       0     .15       0 4212.98     .04       0 4321.04     .08       0
#XS Ineff= 2 , 0
       0    4182            4682       0
Permanent Ineff=
       T       T
Bank Sta=4212.98,4321.04
XS Rating Curve= 0
Exp/Cntr=.3,.1

Type RM Length L Ch R = 1 ,11488   ,890.75,783.01,452.24
BEGIN DESCRIPTION:
 11487.65--surveyed channel
END DESCRIPTION:
XS GIS Cut Line= 6
     3039124.674    13832215.387     3038621.212    13830509.019
     3037049.916    13829241.809     3037039.629     13829087.56
       3035741.6    13828263.806     3029607.173    13828125.853
#Sta/Elev= 30
       0   85.24   48.33   81.79  910.53   83.78 1283.87   79.73 2119.33   81.49
 2215.68    78.7 2609.76   78.22  3062.8   80.89 3140.65   78.36 3275.54   81.43
 3541.64   78.71 3756.69   81.85 3831.66   79.55 3883.35   66.83 3934.36      81
 4525.27   78.47 4685.16   81.71 6041.76   85.01 6281.82    82.2 6716.93   85.31
 7316.67   83.67 7677.17    85.1  7782.2   88.81 7853.89   83.97 7884.59   87.09
 8682.42    88.810524.61   90.2110707.94    87.310827.97   90.23 11633.5   91.13
#Mann= 3 , 0 , 0
       0     .15       0 3831.66     .04       0 3934.36     .15       0
#XS Ineff= 2 , 0
       0    3812            3958       0
Permanent Ineff=
       T       T
Bank Sta=3831.66,3934.36
XS Rating Curve= 0
Exp/Cntr=.3,.1

Type RM Length L Ch R = 1 ,10705   ,254.87,356.01,358.45
BEGIN DESCRIPTION:
 10704.64--surveyed channel
END DESCRIPTION:
XS GIS Cut Line= 6
     3039148.549    13832199.471     3038840.607    13829837.928
     3037937.215    13828702.235     3037085.446    13828611.896
       3035748.5     13828194.83     3029503.668    13828070.672
#Sta/Elev= 30
       0   84.57  652.45    82.1  803.72   84.82  833.97   89.24  894.48   90.86
  1015.5   82.89 1647.83   79.71 3510.98   78.21 4264.62   81.83  4289.4    80.2
 4364.48   66.29  4379.8   67.83 4421.26   80.08 5829.33   80.41 5913.15   83.26
 6611.28   85.06 6881.33   82.38 7931.54   84.18 8364.51   88.82 8456.35   84.04
 8486.65   87.42 9175.79   86.88 9566.86   91.6110076.96    86.610332.01   90.61
10400.37    88.211157.17   89.89 11303.5   87.4411471.88   90.2112336.24   91.09
#Mann= 3 , 0 , 0
       0     .15       0 4264.62     .04       0 4421.26     .15       0
#XS Ineff= 2 , 0
       0    4264            4494       0
Permanent Ineff=
       T       T
Bank Sta=4264.62,4421.26
XS Rating Curve= 0
Exp/Cntr=.3,.1

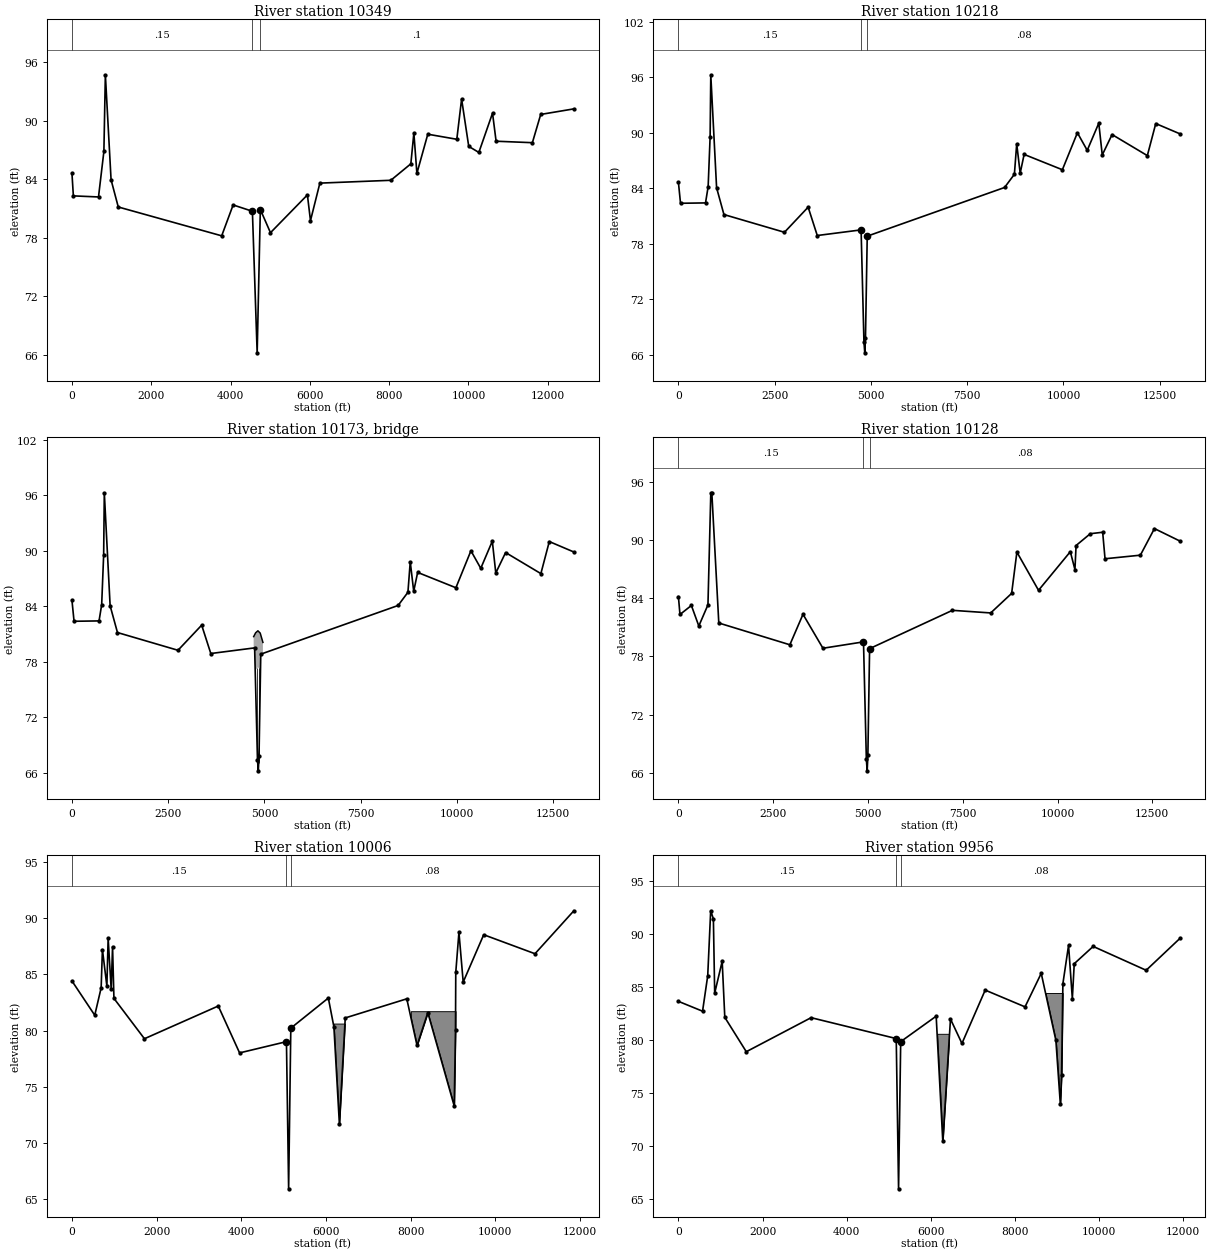
Type RM Length L Ch R = 1 ,10349   ,196.29,130.22,126.02
BEGIN DESCRIPTION:
10348.64--u/s approach Richmond Avenue bridge; channel copied from 10128
END DESCRIPTION:
XS GIS Cut Line= 6
     3039155.021    13832202.995     3038842.038     13829668.85
     3037949.075     13828360.07     3037508.735     13828279.61
     3035789.902    13828146.546     3029441.565    13828036.184
#Sta/Elev= 30
       0   84.61   35.72   82.29  669.73   82.18  805.59   86.85   842.9   94.72
   986.8   83.94 1168.31   81.15 3776.94   78.19 4065.46   81.36  4551.5   80.71
 4671.65   66.18 4751.74   80.89 5007.48   78.51 5938.93   82.39 6016.52   79.75
 6253.33    83.6 8042.96   83.89 8547.89   85.58 8624.22   88.74 8700.56    84.6
 8975.38   88.62 9707.31    88.1 9828.23   92.2310008.26   87.37 10263.3   86.75
10608.35   90.7810698.36    87.9 11613.5   87.7511823.53   90.6512659.59   91.22
#Mann= 3 , 0 , 0
       0     .15       0  4551.5     .04       0 4751.74      .1       0
#XS Ineff= 2 , 0
       0    4540            4791       0
Permanent Ineff=
       T       T
Bank Sta=4551.5,4751.74
XS Rating Curve= 0
Exp/Cntr=.5,.3

Type RM Length L Ch R = 1 ,10218   ,127.92,90.26,93.95
BEGIN DESCRIPTION:
10218.42--u/s face Richmond Avenue bridge; channel copied from 10128
END DESCRIPTION:
XS GIS Cut Line= 6
     3039164.465    13832207.429     3038843.583     13829443.63
     3038025.953     13828241.97     3037520.514     13828149.61
     3037312.109     13828149.61     3029241.454    13827829.255
#Sta/Elev= 30
       0   84.64   54.63   82.37  703.83   82.41  772.17   84.17  823.42   89.57
  840.51   96.28  991.54   84.05 1182.19   81.15 2753.94   79.23 3369.17   81.95
 3606.21   78.88 4744.36   79.49 4818.37   67.38 4839.65   66.18 4858.23   67.77
 4903.88   78.81 8470.64   84.08 8725.82   85.51 8785.87   88.81 8875.93   85.62
 8978.24   87.66 9971.74      8610362.03      9010617.22    88.110917.44   91.04
11007.51    87.6 11262.7   89.8112178.37   87.5312397.25      9113035.06   89.87
#Mann= 3 , 0 , 0
       0     .15       0 4744.36     .04       0 4903.88     .08       0
#XS Ineff= 2 , 0
       0    4712            5004       0
Permanent Ineff=
       T       T
Bank Sta=4744.36,4903.88
XS Rating Curve= 0
Exp/Cntr=.5,.3

Type RM Length L Ch R = 3 ,10173   ,,,
BEGIN DESCRIPTION:
Richmond Avenue Bridge (modeled as single structure)
END DESCRIPTION:
Bridge Culvert--1,0,-1,-1, 0
Deck Dist Width WeirC Skew NumUp NumDn MinLoCord MaxHiCord MaxSubmerge Is_Ogee
5,80,2.6,0, 5, 5, , , .95, 0, 0,0,,
  4719.5 4769.66 4829.66 4889.66    4960
   80.71   81.12   81.34   81.09   80.08
           77.08   77.38   77.17
  4858.5 4908.66 4968.66 5028.66    5099
   80.71   81.12   81.34   81.09   80.08
           77.08   77.38   77.17
Pier Skew, UpSta & Num, DnSta & Num=  ,4809.66, 2 ,4948.66, 2 , 0 , 0 , 0 ,,
     1.5     1.5
       0     100
     1.5     1.5
       0     100
Pier Skew, UpSta & Num, DnSta & Num=  ,4849.66, 2 ,4988.66, 2 , 0 , 0 , 0 ,,
     1.5     1.5
       0     100
     1.5     1.5
       0     100
BR Coef=-1 , 1 , 1 ,1.25, 0 ,,,.8,-1,2,0,
WSPro=,,,, 1 ,,,, 0 ,,,, 0 ,,,,-1 ,-1 ,-1 , 0 , 0 , 0 , 0 , 0
BC Design=,, 0 ,, 0 ,,,,,,

Type RM Length L Ch R = 1 ,10128   ,157.07,121.91,186.06
BEGIN DESCRIPTION:
10128.16--d/s face Richmond Avenue bridge; surveyed channel
END DESCRIPTION:
XS GIS Cut Line= 6
     3039199.765    13832208.109     3038930.947    13829412.043
     3038079.177      13828160.2     3037528.669    13828059.614
     3032995.254    13827863.743     3029179.351    13827739.586
#Sta/Elev= 30
       0   84.19    40.8   82.34  342.18   83.27  538.08   81.15  779.19   83.34
  854.53   94.92  881.78   94.88 1065.17   81.46 2939.52   79.21 3286.19   82.36
 3812.32   78.85  4881.7   79.51 4957.37   67.38 4978.65   66.18 4997.23   67.77
 5042.88   78.81 7227.25   82.77 8237.16    82.5 8789.18   84.52 8927.77   88.79
 9498.45   84.8410337.46   88.8310458.96   86.9810488.97   89.4710864.17   90.69
11190.66   90.8411252.71    88.112184.87   88.4712555.78   91.2213238.58   89.91
#Mann= 3 , 0 , 0
       0     .15       0  4881.7     .04       0 5042.88     .08       0
#XS Ineff= 2 , 0
       0    4865            5291       0
Permanent Ineff=
       T       T
Bank Sta=4881.7,5042.88
XS Rating Curve= 0
Exp/Cntr=.5,.3

Type RM Length L Ch R = 1 ,10006   ,102.11,49.94,44.42
BEGIN DESCRIPTION:
10006.25--d/s exit Richmond Avenue bridge; channel copied from 9956
END DESCRIPTION:
XS GIS Cut Line= 6
     3039226.235    13832195.571     3039037.984     13829532.45
      3038096.73    13828021.424     3037343.833    13827928.142
     3036082.578    13827411.913     3030802.916    13827362.457
#Sta/Elev= 30
       0   84.42  538.66   81.37  689.79   83.81  719.86   87.21  825.12   83.96
   855.2   88.21  927.01   83.68  959.37   87.47  991.73   82.87 1712.33   79.28
 3456.43   82.19 3960.16   78.02  5067.2   79.02 5118.81   65.93  5170.2   80.22
 6056.74    82.9 6187.94   80.34 6317.61   71.72  6456.5   81.13 7910.06   82.83
 8151.99   78.68 8407.01    81.6  9030.6    73.3 9060.89   80.03 9067.04   85.18
 9142.04   88.74  9242.6   84.32 9727.06   88.5310938.56   86.8411856.74   90.66
#Mann= 3 , 0 , 0
       0     .15       0  5067.2     .04       0  5170.2     .08       0
#XS Ineff= 2 , 0
       0    5026            5663       0
Permanent Ineff=
       T       T
#Block Obstruct= 2 ,-1
 6100.76  6485.5   80.63 8006.11 9087.02   81.73
Bank Sta=5067.2,5170.2
XS Rating Curve= 0
Exp/Cntr=.3,.1

Type RM Length L Ch R = 1 ,9956    ,327.89,424.48,417.3
BEGIN DESCRIPTION:
 9956.31--surveyed channel
END DESCRIPTION:
XS GIS Cut Line= 6
     3039287.974    13832202.995     3039111.625    13829528.194
     3038150.957    13827965.157     3037340.742    13827879.674
     3036079.717    13827360.216     3030845.148    13827311.183
#Sta/Elev= 30
       0   83.61  574.03   82.68  697.01   86.03  767.15   92.15  831.53   91.39
  862.36   84.38 1040.74   87.39 1102.88    82.1 1613.99   78.86 3155.12   82.07
 5179.15    80.1 5234.81   65.93 5285.32   79.81 6128.92   82.21 6286.45   70.41
 6469.27   81.94 6741.61   79.64  7294.5   84.67 8241.68   83.09 8627.04   86.25
 8975.31   79.93 9081.31   73.93  9111.6   76.68 9141.72   85.27 9276.73   88.89
 9366.73   83.87 9411.73   87.16 9861.75   88.7911121.81   86.5411934.19   89.58
#Mann= 3 , 0 , 0
       0     .15       0 5179.15     .04       0 5285.32     .08       0
#XS Ineff= 2 , 0
       0    5145            5770       0
Permanent Ineff=
       T       T
#Block Obstruct= 2 ,-1
  6137.4 6430.53   80.55 8738.93 9196.95    84.4
Bank Sta=5179.15,5285.32
XS Rating Curve= 0
Exp/Cntr=.3,.1