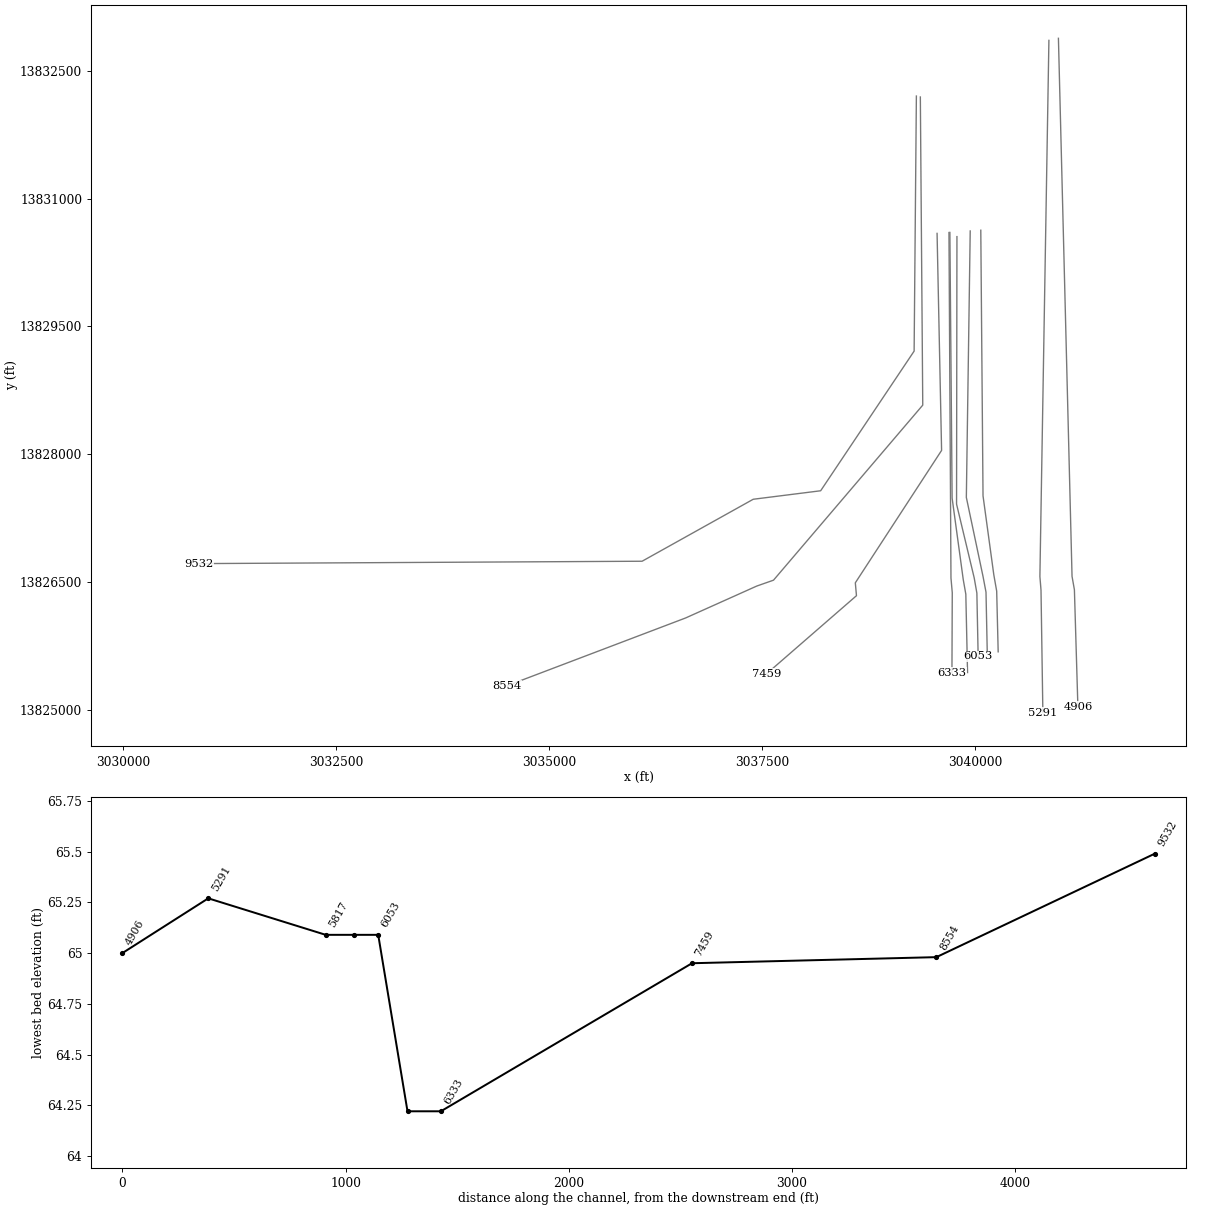
HEC-RAS study D129-00-00.prj: D129-00-00

--- D129-00-00.g02 (geometry) --- (continued)

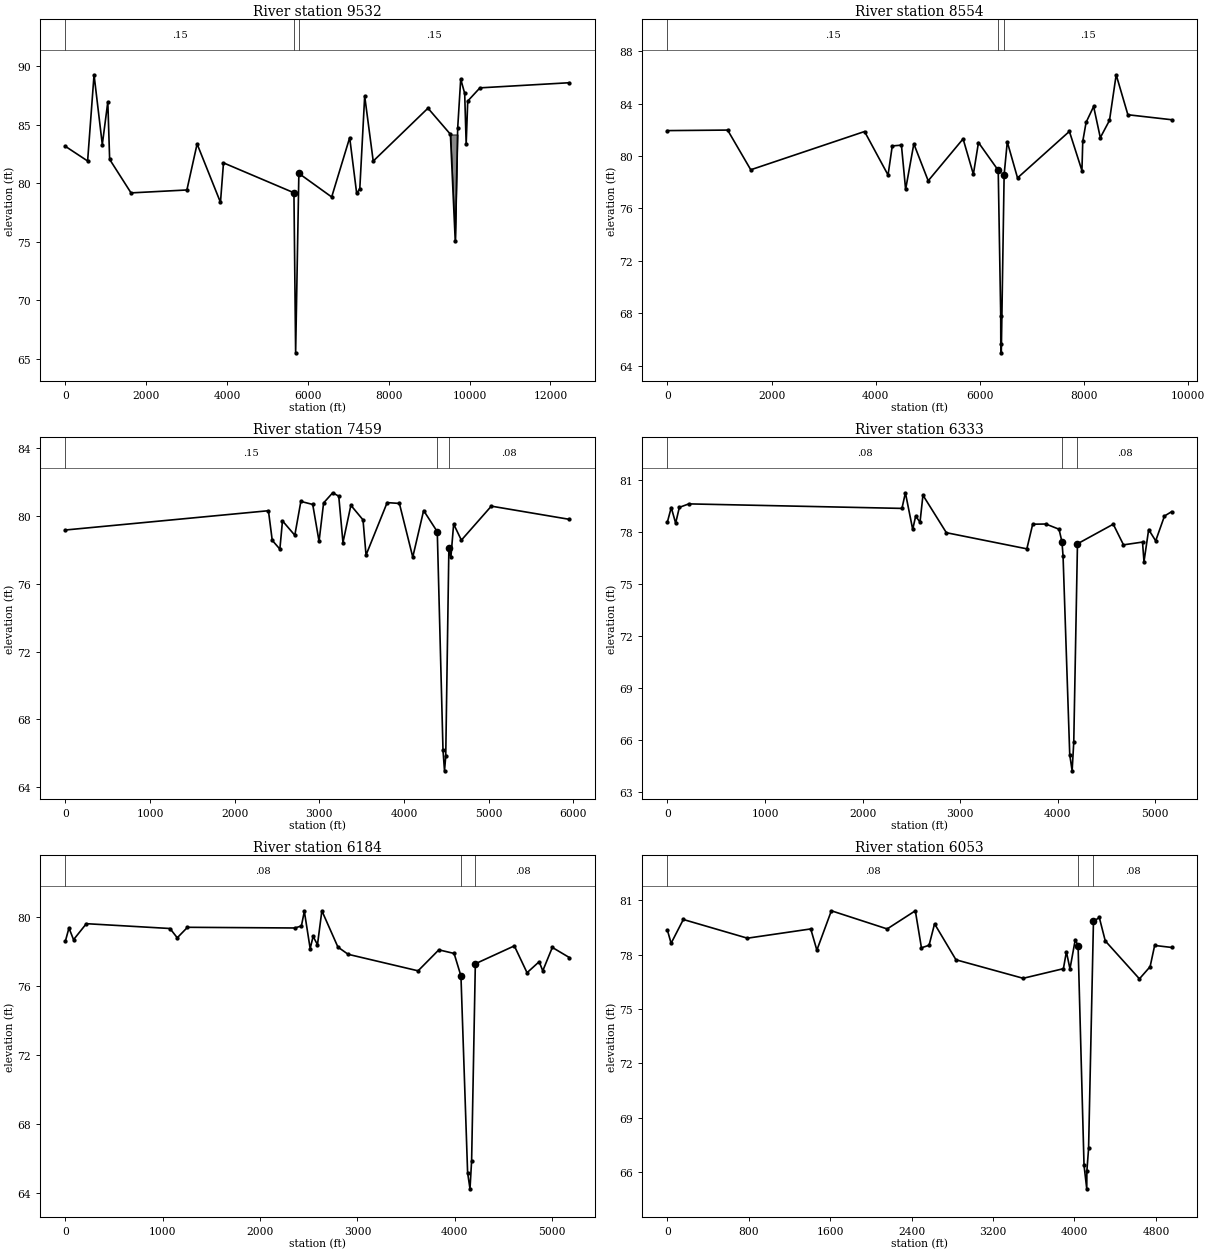
Type RM Length L Ch R = 1 ,9532    ,297.68,978.23,1007.11
BEGIN DESCRIPTION:
 9531.826--surveyed channel
END DESCRIPTION:
XS GIS Cut Line= 6
     3039306.167    13832203.044     3039279.694    13829209.438
     3038182.718    13827570.427     3037391.306    13827470.701
     3036086.913    13826743.313     3030888.658    13826715.526
#Sta/Elev= 30
       0   83.17  551.78   81.91  710.57   89.29     915   83.32 1051.21   86.97
 1096.62   82.05 1625.61   79.18 3007.12   79.43  3259.6   83.37 3837.58   78.37
  3912.4   81.75 5654.69   79.19 5696.64   65.49 5776.67   80.85 6588.23   78.83
 7033.59   83.91 7206.52   79.13 7283.84   79.54 7404.48   87.47 7615.61    81.9
  8969.6   86.43  9524.6    84.2 9644.61   75.04 9704.61   84.72 9779.61   88.92
 9877.74    87.7 9914.61   83.36 9953.14   87.0410254.76   88.1712468.49   88.61
#Mann= 3 , 0 , 0
       0     .15       0 5654.69     .04       0 5776.67     .15       0
#XS Ineff= 2 , 0
       0    5616            5800       0
Permanent Ineff=
       T       T
#Block Obstruct= 1 ,-1
 9447.33 9725.19   84.18
Bank Sta=5654.69,5776.67
XS Rating Curve= 0
Exp/Cntr=.3,.1

Type RM Length L Ch R = 1 ,8554    ,655.15,1094.92,984.21
BEGIN DESCRIPTION:
8553.598--surveyed channel
END DESCRIPTION:
XS GIS Cut Line= 6
     3039352.701    13832191.948     3039380.966    13828575.435
     3037629.302    13826520.976     3037431.997    13826451.683
     3036597.245    13826077.256     3034502.965    13825282.096
#Sta/Elev= 30
       0   81.94 1155.25   81.98  1599.5   78.95 3784.75   81.87 4236.03   78.55
 4316.97   80.77  4492.8   80.83 4573.23   77.45 4730.92   80.93 5006.89   78.11
  5677.1   81.31 5874.22   78.61 5972.45   81.03 6351.54   78.91 6399.45   67.82
 6401.01   65.62 6410.86   64.98 6465.18   78.58 6525.58   81.08 6722.31   78.33
  7718.3   81.88 7958.97   78.89 7975.01   81.12 8039.19   82.57  8183.6   83.78
 8311.95    81.4 8488.45   82.72  8616.8    86.2 8841.43   83.15 9680.61   82.77
#Mann= 3 , 0 , 0
       0     .15       0 6351.54     .04       0 6465.18     .15       0
#XS Ineff= 2 , 0
       0    6288            6521       0
Permanent Ineff=
       F       F
Bank Sta=6351.54,6465.18
XS Rating Curve= 0
Exp/Cntr=.3,.1

Type RM Length L Ch R = 1 ,7459    ,431.1,1125.38,1863.09
BEGIN DESCRIPTION:
 7458.677--surveyed channel
END DESCRIPTION:
XS GIS Cut Line= 5
     3039549.068     13830591.22     3039602.038     13828044.05
     3038589.526     13826490.05     3038602.971    13826338.857
     3037545.959    13825420.452
#Sta/Elev= 30
       0   79.18 2399.24   80.32 2444.25   78.57 2534.27   78.05 2565.19   79.72
  2710.7   78.87 2782.31   80.87  2922.4   80.69 2997.15   78.51 3050.85   80.78
 3158.27   81.38 3229.88   81.18 3279.61   78.44 3373.11   80.64 3516.33   79.78
 3552.14    77.7 3801.68    80.8    3946   80.75 4103.93   77.58 4232.45   80.33
 4393.58   79.08 4461.02    66.2 4478.94   64.95 4493.37    65.8 4530.65   78.12
 4554.26   77.56 4586.82   79.53  4678.3   78.58 5031.79   80.59 5954.52   79.81
#Mann= 3 , 0 , 0
       0     .15       0 4393.58     .04       0 4530.65     .08       0
#XS Ineff= 2 , 0
       0    4390            5592       0
Permanent Ineff=
       T       T
Bank Sta=4393.58,4530.65
XS Rating Curve= 0
Exp/Cntr=.3,.1

Type RM Length L Ch R = 1 ,6333    ,18.78,149.46,174.33
BEGIN DESCRIPTION:
 6333.299--surveyed channel
END DESCRIPTION:
XS GIS Cut Line= 4
      3039688.73    13830601.367     3039712.123    13826546.303
     3039727.318     13826374.17      3039723.55    13825434.574
#Sta/Elev= 30
       0   78.57   38.87   79.39   83.87   78.49  121.94    79.4  218.87    79.6
 2403.81   79.34 2438.91   80.24 2513.91   78.13 2543.91   78.89 2588.91   78.55
 2618.91    80.1 2858.91   77.94 3683.93   77.01 3743.93   78.43 3878.93   78.44
 4013.93   78.14 4043.93   77.41 4055.13   76.59  4123.5   65.16    4148   64.22
 4164.73   65.86 4202.84    77.3 4569.61   78.43 4674.61   77.24 4869.61    77.4
 4884.61   76.27 4932.62   78.12 5004.61   77.47 5094.61    78.9 5167.54   79.15
#Mann= 3 , 0 , 0
       0     .08       0 4043.93     .04       0 4202.84     .08       0
#XS Ineff= 2 , 0
       0    3855            5166       0
Permanent Ineff=
       T       T
Bank Sta=4043.93,4202.84
XS Rating Curve= 0
Exp/Cntr=.3,.1

Type RM Length L Ch R = 1 ,6184    ,52.7,131.25,129.5
BEGIN DESCRIPTION:
6183.842--u/s approach Eldridge Parkway bridge; channel copied from 6333
END DESCRIPTION:
XS GIS Cut Line= 6
     3039699.331    13830602.137     3039725.531     13827484.84
     3039856.137     13826528.55     3039869.448     13826452.91
     3039886.372     13826357.03     3039906.624    13825436.846
#Sta/Elev= 30
       0    78.6   37.49   79.38   84.64    78.7     216   79.63 1074.67   79.35
 1149.68   78.81 1254.68   79.42 2358.07   79.38 2424.72    79.5 2454.72   80.35
 2514.73   78.18 2544.73   78.89 2589.73   78.41 2634.73   80.38 2799.74   78.27
 2904.74   77.85 3622.95   76.89 3836.08   78.11  3992.8    77.9 4063.13   76.59
  4131.5   65.16    4156   64.22 4172.73   65.86 4210.84    77.3 4611.36   78.34
 4741.84   76.78 4866.42   77.42 4903.33   76.89 5001.45   78.25 5177.15   77.66
#Mann= 3 , 0 , 0
       0     .08       0 4063.13     .04       0 4210.84     .08       0
#XS Ineff= 2 , 0
       0    3805            5101       0
Permanent Ineff=
       T       T
Bank Sta=4063.13,4210.84
XS Rating Curve= 0
Exp/Cntr=.5,.3

Type RM Length L Ch R = 1 ,6053    ,115.1,107.42,108.45
BEGIN DESCRIPTION:
6052.590--u/s face Eldridge Parkway bridge; channel copied from 5945
END DESCRIPTION:
XS GIS Cut Line= 6
      3039782.26    13830553.349     3039777.724     13827413.75
     3039984.602     13826548.62     3039997.471      13826475.5
     3040016.118      13826369.8     3040031.196    13825626.514
#Sta/Elev= 30
       0   79.33   35.85   78.62  155.85   79.93  785.85    78.9 1408.12   79.41
 1468.21   78.24 1610.85   80.41 2159.21   79.41 2435.85   80.41 2495.85   78.37
 2570.85   78.51 2624.88   79.69 2835.19   77.71 3495.61   76.69 3891.09   77.22
 3920.44   78.15 3955.59   77.21 4007.56   78.82 4035.34   78.48 4093.69   66.39
 4120.58   65.09 4121.77   66.08 4138.53   67.32 4186.38   79.82 4243.72   80.04
 4302.54   78.75 4638.09   76.66 4743.11   77.33 4787.79    78.5 4954.14   78.39
#Mann= 3 , 0 , 0
       0     .08       0 4035.34     .04       0 4186.38     .08       0
#XS Ineff= 2 , 0
       0    3737            4951       0
Permanent Ineff=
       T       T
Bank Sta=4035.34,4186.38
XS Rating Curve= 0
Exp/Cntr=.5,.3

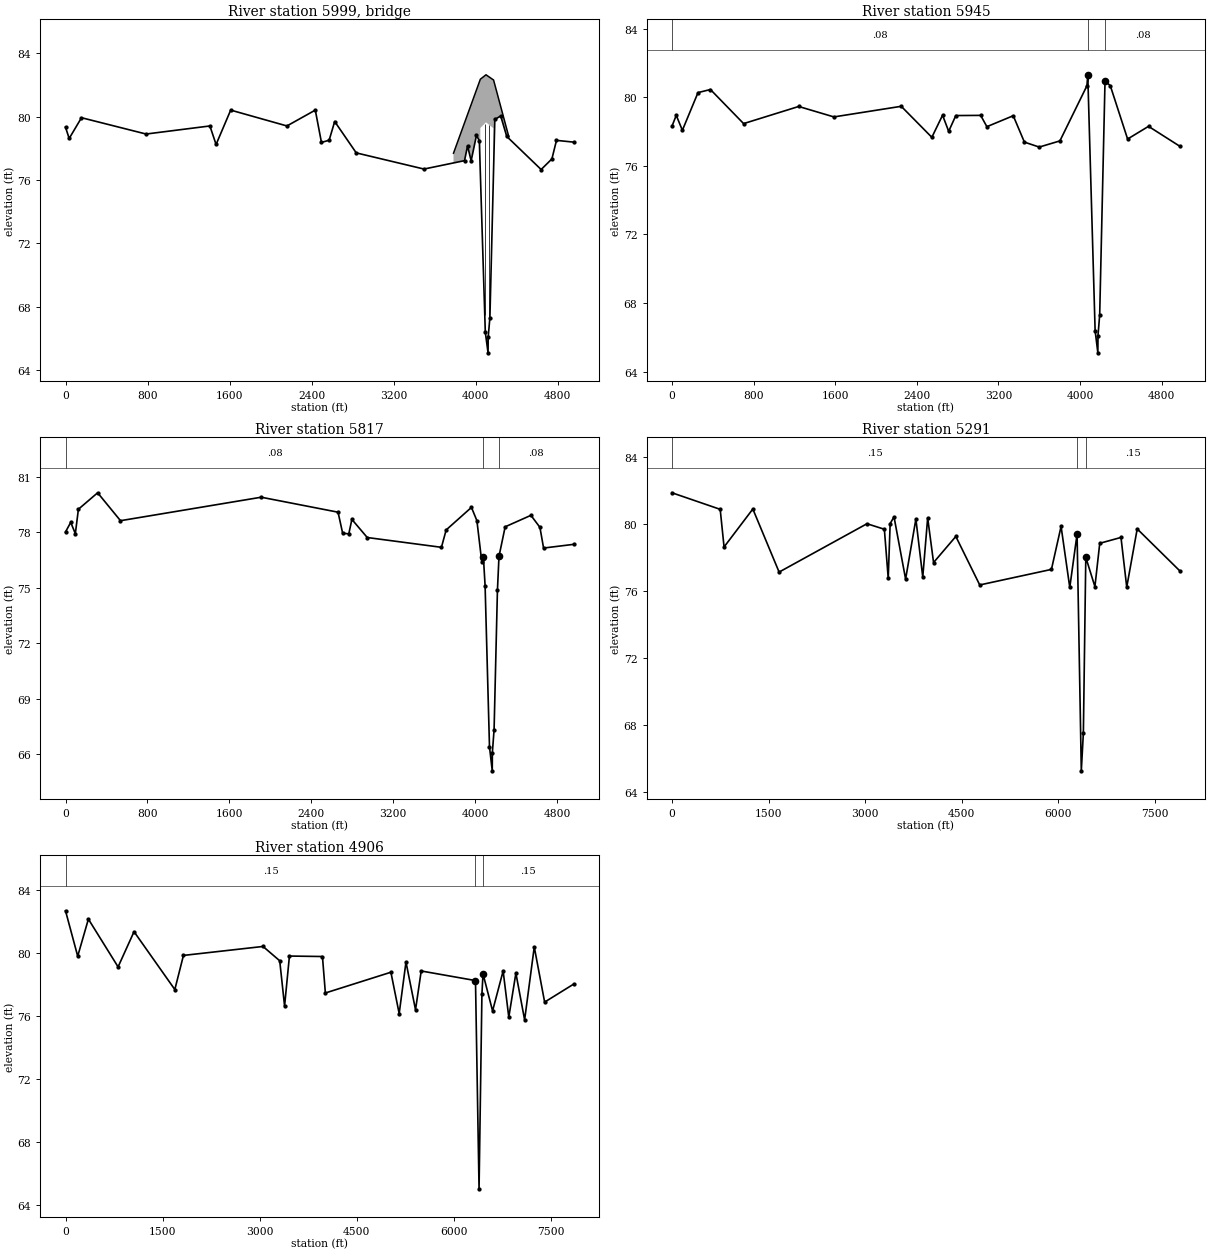
Type RM Length L Ch R = 3 ,5999    ,,,
BEGIN DESCRIPTION:
Eldridge Parkway Bridge (modeled as single structure)
END DESCRIPTION:
Bridge Culvert--1,0,-1,-1, 0
Deck Dist Width WeirC Skew NumUp NumDn MinLoCord MaxHiCord MaxSubmerge Is_Ogee
7,93,2.6,0, 5, 5, , , .95, 0, 0,0,,
  3783.5 4045.29 4100.29 4174.29    4323
   77.69   82.36   82.64   82.31   78.73
           79.28   79.64   79.26
  3837.5 4099.29 4154.29 4228.29    4377
   77.69   82.36   82.64   82.31   78.73
           79.28   79.64   79.26
Pier Skew, UpSta & Num, DnSta & Num=  ,4088.29, 2 ,4142.29, 2 , 0 , 0 , 0 ,,
     1.3     1.3
       0     100
     1.3     1.3
       0     100
Pier Skew, UpSta & Num, DnSta & Num=  ,4131.29, 2 ,4185.29, 2 , 0 , 0 , 0 ,,
     1.3     1.3
       0     100
     1.3     1.3
       0     100
BR Coef=-1 , 1 , 1 ,1.25, 0 ,,,.8,-1,2,0,
WSPro=,,,, 1 ,,,, 0 ,,,, 0 ,,,,-1 ,-1 ,-1 , 0 , 0 , 0 , 0 , 0
BC Design=,, 0 ,, 0 ,,,,,,

Type RM Length L Ch R = 1 ,5945    ,196.62,127.79,128.76
BEGIN DESCRIPTION:
5945.166--d/s face Eldridge Parkway bridge;  surveyed channel
END DESCRIPTION:
XS GIS Cut Line= 5
     3039938.027    13830619.532     3039892.545    13827492.332
     3040088.366    13826564.732     3040123.274    13826380.298
     3040138.164    13825663.901
#Sta/Elev= 30
       0   78.32   42.04   78.95  102.04   78.08  255.24   80.28  377.03   80.46
  702.11   78.47 1242.16   79.47  1587.2   78.86 2247.27   79.48  2547.3   77.67
 2652.31   78.96 2712.32   78.02 2782.26   78.94 3025.83   78.95 3086.72   78.29
 3345.17   78.93 3454.41   77.39 3599.93    77.1 3802.46   77.46 4067.64   80.68
 4075.57   81.32 4147.69   66.39 4174.58   65.09 4175.77   66.08 4192.53   67.32
  4244.7   80.95 4296.09   80.69 4466.14   77.57 4671.17   78.31 4979.83   77.14
#Mann= 3 , 0 , 0
       0     .08       0 4075.57     .04       0  4244.7     .08       0
#XS Ineff= 2 , 0
       0    3802            4915       0
Permanent Ineff=
       T       T
Bank Sta=4075.57,4244.7
XS Rating Curve= 0
Exp/Cntr=.5,.3

Type RM Length L Ch R = 1 ,5817    ,687.26,526.27,519.24
BEGIN DESCRIPTION:
5817.372--d/s exit Eldridge Parkway bridge; channel copied from 5945
END DESCRIPTION:
XS GIS Cut Line= 6
     3040062.124    13830628.497     3040088.323     13827511.03
     3040214.853     13826584.59     3040243.801     13826420.38
     3040248.662      13826392.7     3040266.226    13825679.998
#Sta/Elev= 30
       0   78.01      51   78.53      96   77.92     126   79.24  313.75   80.13
  536.88   78.62 1911.06   79.89 2661.09   79.08 2706.09   77.94 2766.09   77.91
  2796.1   78.69  2946.1   77.71 3670.54   77.18 3716.62   78.12 3963.58   79.34
 4016.86   78.62 4064.89   76.37 4080.13   76.65 4096.74   75.11 4139.69   66.39
 4166.58   65.09 4167.77   66.08 4184.53   67.32 4217.21   74.85 4232.44   76.69
 4292.68   78.29 4544.28   78.91 4632.14   78.26 4667.79   77.14 4960.38   77.34
#Mann= 3 , 0 , 0
       0     .08       0 4080.13     .04       0 4232.44     .08       0
#XS Ineff= 2 , 0
       0    3874            4741       0
Permanent Ineff=
       T       T
Bank Sta=4080.13,4232.44
XS Rating Curve= 0
Exp/Cntr=.3,.1

Type RM Length L Ch R = 1 ,5291    ,335.54,384.82,405.57
BEGIN DESCRIPTION:
 5291.104--surveyed channel
END DESCRIPTION:
XS GIS Cut Line= 4
     3040861.587    13832856.609     3040755.808     13826564.21
       3040768.9    13826403.899     3040790.758    13824965.617
#Sta/Elev= 30
       0   81.89  749.21    80.9  809.22   78.65 1256.32   80.92 1664.34   77.15
 3029.54   80.04 3299.58   79.71 3359.58   76.78 3389.59   80.05  3449.6   80.45
 3629.62   76.73 3789.25   80.32 3896.06   76.85 3972.35   80.39  4063.9   77.72
 4409.73   79.28 4781.06   76.38 5895.16   77.31 6044.96   79.88 6179.98   76.23
 6293.29   79.42 6359.19   65.27 6391.23   67.54 6428.88   78.03 6570.55   76.28
 6645.55   78.87 6975.59   79.22 7064.92   76.25 7227.47   79.73 7892.58   77.21
#Mann= 3 , 0 , 0
       0     .15       0 6293.29     .04       0 6428.88     .15       0
#XS Ineff= 2 , 0
       0    6290            6490       0
Permanent Ineff=
       T       T
Bank Sta=6293.29,6428.88
XS Rating Curve= 0
Exp/Cntr=.3,.1

Type RM Length L Ch R = 1 ,4906    ,89.5,101.33,104.89
BEGIN DESCRIPTION:
4906.282--u/s appraoch Synott Road bridge; channel copied from 4762
END DESCRIPTION:
XS GIS Cut Line= 6
     3040973.303    13832880.896     3041133.089     13826566.06
     3041148.332     13826479.48     3041150.395     13826467.84
     3041160.898     13826408.29     3041201.787    13825037.013
#Sta/Elev= 30
       0   82.69  188.46    79.8  353.51   82.16  812.31   79.12 1058.74   81.36
 1688.94   77.68 1822.09   79.85 3051.39   80.42 3309.46   79.51 3384.48   76.63
 3459.51   79.81 3969.67   79.78 4014.68   77.46 5027.04   78.78 5155.05   76.15
 5260.08   79.43 5407.54   76.39 5495.35   78.86 6333.97   78.25    6389      65
 6433.41   77.39 6450.13   78.68 6597.91   76.32 6761.12   78.86 6848.55   75.92
 6958.07   78.72 7093.13   75.75    7242   80.39 7402.29   76.88 7848.95   78.02
#Mann= 3 , 0 , 0
       0     .15       0 6333.97     .04       0 6450.13     .15       0
#XS Ineff= 2 , 0
       0    6316            6480       0
Permanent Ineff=
       T       T
Bank Sta=6333.97,6450.13
XS Rating Curve= 0
Exp/Cntr=.5,.3