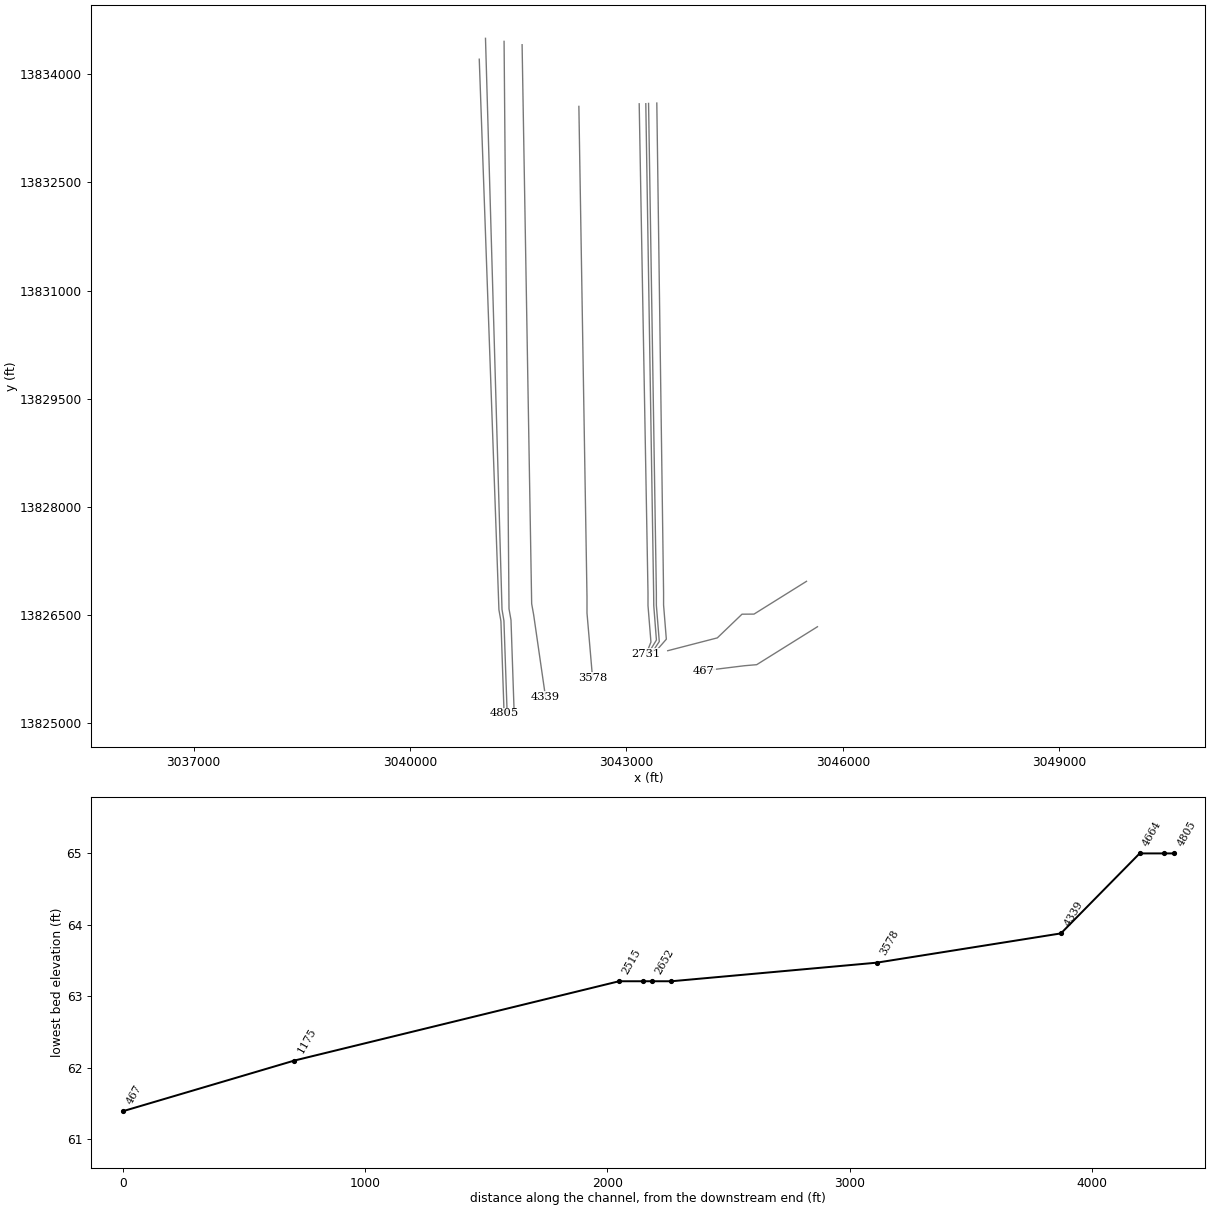
HEC-RAS study D129-00-00.prj: D129-00-00

--- D129-00-00.g02 (geometry) --- (continued)

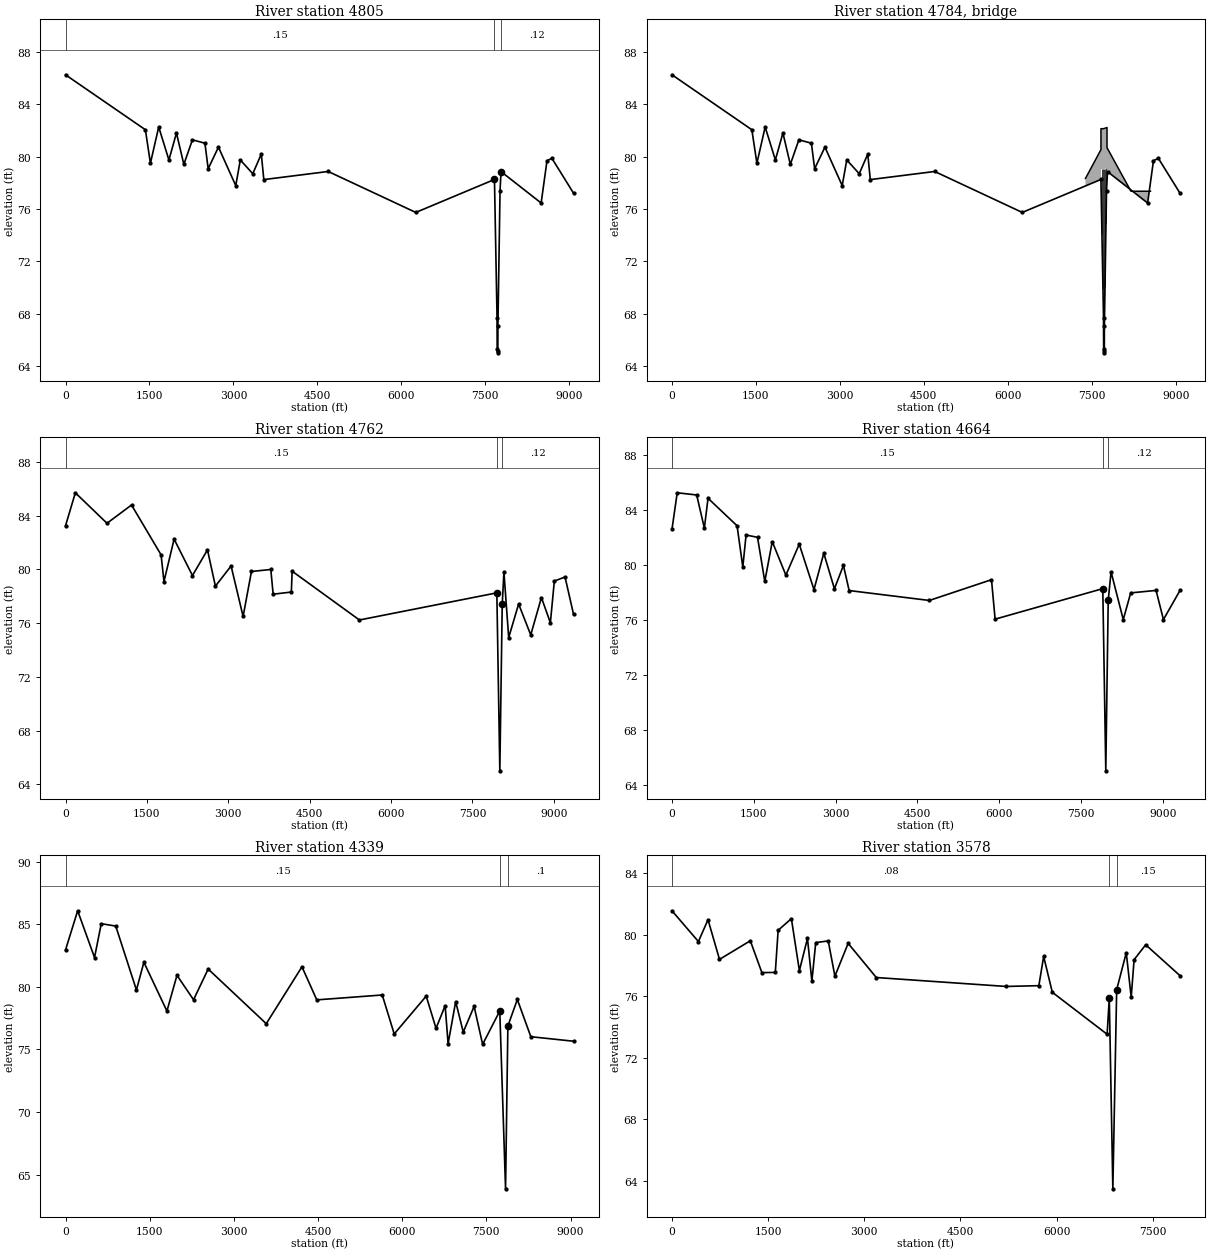
Type RM Length L Ch R = 1 ,4805    ,50.01,42.78,43.37
BEGIN DESCRIPTION:
4804.954--u/s face Synott Road bridge; channel copied from 4762
END DESCRIPTION:
XS GIS Cut Line= 6
     3040960.202    13834208.859     3041233.015     13826575.21
     3041246.814     13826496.84     3041255.675     13826446.59
     3041260.599     13826418.75     3041304.317     13825138.92
#Sta/Elev= 30
       0   86.25 1427.27   82.05 1517.33   79.49 1665.24   82.26 1847.54   79.74
 1982.62    81.8 2114.49    79.4 2267.81   81.28 2491.27   81.02 2549.24   79.07
  2733.1   80.72 3041.96   77.78 3123.35   79.74 3346.28   78.69 3498.59   80.19
 3543.62   78.24 4694.01   78.86 6259.11   75.73 7664.97   78.25 7710.94   67.69
 7713.41   65.26    7720      65 7725.43   65.12  7726.6   67.03 7764.41   77.39
 7782.37   78.85 8499.06   76.45  8603.5   79.68 8690.58   79.87 9077.98    77.2
#Mann= 3 , 0 , 0
       0     .15       0 7664.97     .04       0 7782.37     .12       0
#XS Ineff= 2 , 0
       0    7647            7811       0
Permanent Ineff=
       T       T
Bank Sta=7664.97,7782.37
XS Rating Curve= 0
Exp/Cntr=.5,.3

Type RM Length L Ch R = 3 ,4784    ,,,
BEGIN DESCRIPTION:
Synott Road Bridge
END DESCRIPTION:
Bridge Culvert--1,0,-1,-1, 0
Deck Dist Width WeirC Skew NumUp NumDn MinLoCord MaxHiCord MaxSubmerge Is_Ogee
6,30,2.6,0, 8, 8, , , .95, 0, 0,0,,
 7388.89 7665.42 7665.42 7712.42 7773.42 7773.42 8201.49    8550
   78.33   80.53   82.13   82.13   82.22   80.68   77.35   77.35
                   79.03   79.03   79.12
 7673.89 7950.42 7950.42 7997.42 8058.42 8058.42 8486.49    8835
   78.33   80.53   82.13   82.13   82.22   80.68   77.35   77.35
                   79.03   79.03   79.12
Pier Skew, UpSta & Num, DnSta & Num=  ,7683.42, 2 ,7968.42, 2 , 0 , 0 , 0 ,,
     1.1     1.1
       0     100
     1.1     1.1
       0     100
Pier Skew, UpSta & Num, DnSta & Num=  ,7701.42, 2 ,7986.42, 2 , 0 , 0 , 0 ,,
     1.1     1.1
       0     100
     1.1     1.1
       0     100
Pier Skew, UpSta & Num, DnSta & Num=  ,7719.42, 2 ,8004.42, 2 , 0 , 0 , 0 ,,
     1.1     1.1
       0     100
     1.1     1.1
       0     100
Pier Skew, UpSta & Num, DnSta & Num=  ,7737.42, 2 ,8022.42, 2 , 0 , 0 , 0 ,,
     1.1     1.1
       0     100
     1.1     1.1
       0     100
Pier Skew, UpSta & Num, DnSta & Num=  ,7755.42, 2 ,8040.42, 2 , 0 , 0 , 0 ,,
     1.1     1.1
       0     100
     1.1     1.1
       0     100
BR Coef=-1 , 1 , 1 ,1.25, 0 ,,,.8,-1,2,0,
WSPro=,,,, 1 ,,,, 0 ,,,, 0 ,,,,-1 ,-1 ,-1 , 0 , 0 , 0 , 0 , 0
BC Design=,, 0 ,, 0 ,,,,,,

Type RM Length L Ch R = 1 ,4762    ,118.76,98.46,100.79
BEGIN DESCRIPTION:
4762.171--d/s face Synott Road bridge; surveyed channel
END DESCRIPTION:
XS GIS Cut Line= 4
     3041046.698    13834498.183     3041275.719    13826579.341
       3041302.3    13826423.248     3041347.027    13825140.755
#Sta/Elev= 30
       0   83.24  181.32    85.7   764.7   83.43 1216.82   84.79 1761.42   81.08
 1814.78   79.09 2001.52   82.25 2339.82   79.54 2616.78   81.45 2762.77   78.75
 3051.96   80.25 3273.23   76.49 3427.12   79.84 3783.69   79.99 3827.44   78.15
 4162.42   78.31 4177.43   79.86 5417.15   76.23 7949.97   78.25    8005      65
 8049.41   77.39 8080.49   79.79 8168.43   74.92 8351.41   77.42 8574.52   75.12
 8771.66    77.9 8936.76   76.02 9009.62   79.13 9206.93   79.43 9363.77   76.65
#Mann= 3 , 0 , 0
       0     .15       0 7949.97     .04       0 8049.41     .12       0
#XS Ineff= 2 , 0
       0    7936            8099       0
Permanent Ineff=
       T       T
Bank Sta=7949.97,8049.41
XS Rating Curve= 0
Exp/Cntr=.5,.3

Type RM Length L Ch R = 1 ,4664    ,308.31,324.95,365.87
BEGIN DESCRIPTION:
4663.713--d/s exit Synott Road bridge; channel copied from 4762
END DESCRIPTION:
XS GIS Cut Line= 6
     3041304.335    13834456.288     3041372.912     13826588.03
      3041384.69     13826521.13     3041393.543     13826470.93
      3041400.18      13826433.4     3041444.236      13825143.7
#Sta/Elev= 30
       0   82.56   96.12   85.22  453.02   85.06  593.81   82.65  661.22   84.82
 1193.83   82.82 1298.84   79.82 1358.84   82.15 1568.85   81.98 1702.18   78.77
 1838.86   81.67 2088.83   79.23 2333.88   81.48 2603.89   78.18 2783.89   80.82
  2978.9   78.24 3143.91   79.94 3248.76   78.11 4718.97   77.39 5859.01    78.9
 5925.54   76.03 7899.97   78.25    7955      65 7999.41   77.39 8051.49   79.47
 8275.41      76 8411.69   77.94 8876.97   78.12 9012.05      76 9316.02   78.12
#Mann= 3 , 0 , 0
       0     .15       0 7899.97     .04       0 7999.41     .12       0
#XS Ineff= 2 , 0
       0    7877            8054       0
Permanent Ineff=
       T       T
Bank Sta=7899.97,7999.41
XS Rating Curve= 0
Exp/Cntr=.3,.1

Type RM Length L Ch R = 1 ,4339    ,773.9,760.43,723.76
BEGIN DESCRIPTION:
 4338.764--surveyed channel
END DESCRIPTION:
XS GIS Cut Line= 4
     3041554.209    13834409.552     3041686.952    13826658.885
     3041714.861    13826502.988     3041878.241    13825371.261
#Sta/Elev= 30
       0   82.94  216.66   86.07  517.13   82.34  637.15   85.04  895.15   84.85
 1263.89   79.75 1396.63   81.96 1807.32   78.07 1986.62   80.92 2281.61   78.97
 2542.42   81.42 3577.58   77.06  4213.8    81.6 4477.71   78.96 5644.51   79.35
 5857.91   76.24    6428   79.26 6603.24   76.69 6765.48    78.5 6818.05   75.46
 6953.07   78.82 7088.09   76.39 7281.72   78.44 7433.14   75.41 7738.96   78.07
 7841.95   63.88 7883.46   76.88 8052.12   78.99 8292.59   76.02 9053.64   75.66
#Mann= 3 , 0 , 0
       0     .15       0 7738.96     .04       0 7883.46      .1       0
#XS Ineff= 2 , 0
       0    7730            8028       0
Permanent Ineff=
       T       T
Bank Sta=7738.96,7883.46
XS Rating Curve= 0
Exp/Cntr=.3,.1

Type RM Length L Ch R = 1 ,3578    ,848.34,846.96,850.4
BEGIN DESCRIPTION:
 3578.333--surveyed channel
END DESCRIPTION:
XS GIS Cut Line= 4
     3042341.349    13833554.648     3042453.986     13826753.58
     3042453.986    13826530.811      3042530.82    13825633.884
#Sta/Elev= 30
       0   81.55   412.2   79.55  562.23   80.97  741.13   78.39 1222.32    79.6
 1402.34   77.53 1611.83   77.54  1656.1   80.28 1862.71   81.04 1987.42   77.66
 2113.59   79.75 2182.45   76.97 2242.46   79.48 2437.48   79.59 2541.56    77.3
 2748.17   79.43 3187.58   77.21 5212.69   76.63 5722.93   76.68 5797.94   78.58
 5932.96   76.25 6788.08   73.52 6821.75   75.89 6877.23   63.47 6936.91   76.42
 7086.55   78.82 7163.59   75.93 7208.75   78.37 7389.41   79.34 7924.98   77.33
#Mann= 3 , 0 , 0
       0     .08       0 6821.75     .04       0 6936.91     .15       0
#XS Ineff= 2 , 0
       0    6600            7021       0
Permanent Ineff=
       T       T
Bank Sta=6821.75,6936.91
XS Rating Curve= 0
Exp/Cntr=.3,.1

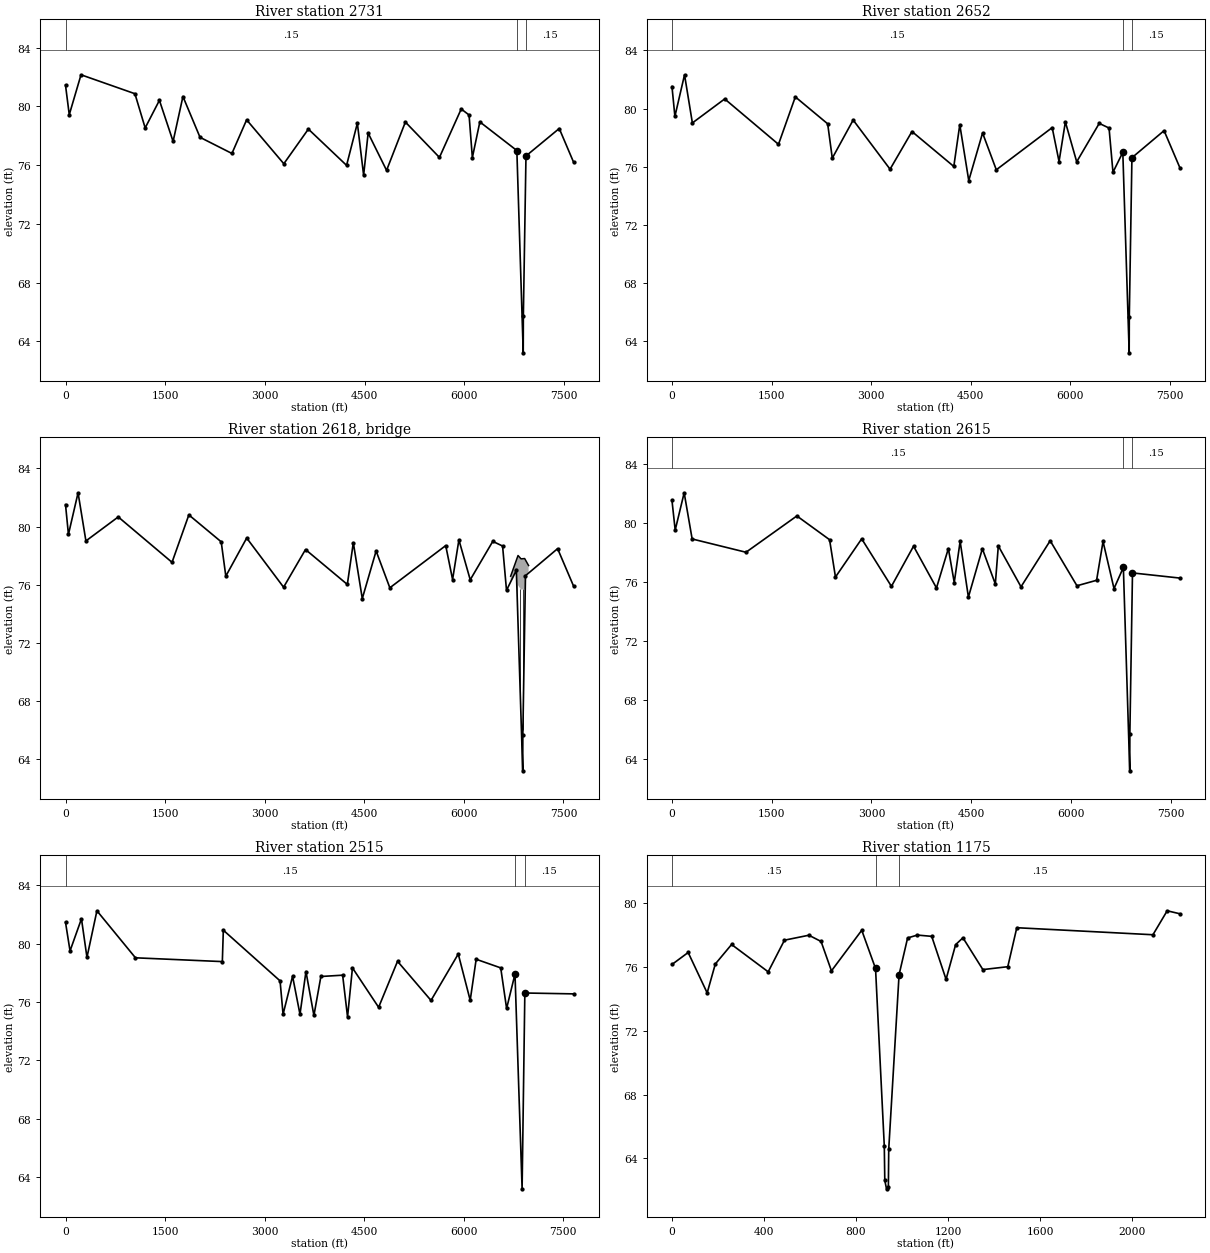
Type RM Length L Ch R = 1 ,2731    ,80.45,79.27,78.77
BEGIN DESCRIPTION:
2731.375--u/s approach S Briarknoll pedestrian bridge; channel copied from 2652
END DESCRIPTION:
XS GIS Cut Line= 6
     3043177.889    13833590.355     3043299.866     13826805.37
     3043299.833     13826668.84      3043299.87     13826632.26
     3043340.583    13826127.138     3043275.651    13825964.918
#Sta/Elev= 30
       0   81.44   56.46   79.43  233.31   82.15 1043.87   80.86 1198.05   78.53
 1412.31   80.41 1618.12   77.61 1766.01   80.67 2023.18   77.89 2502.88   76.79
 2723.94   79.08 3283.39   76.09 3652.41   78.45 4227.17   75.98 4389.28   78.85
 4483.58   75.31 4551.39   78.18 4828.63   75.64 5111.42   78.93 5623.76   76.52
 5951.45   79.82 6069.35   79.41 6118.84   76.51 6231.46   78.94 6787.94   76.99
 6883.97   63.21 6885.71    65.7 6925.27   76.62 7425.46   78.49 7640.68    76.2
#Mann= 3 , 0 , 0
       0     .15       0 6787.94     .04       0 6925.27     .15       0
#XS Ineff= 2 , 0
       0    6780            6972       0
Permanent Ineff=
       T       T
Bank Sta=6787.94,6925.27
XS Rating Curve= 0
Exp/Cntr=.5,.3

Type RM Length L Ch R = 1 ,2652    ,38.06,36.92,37.28
BEGIN DESCRIPTION:
2652.108--u/s face S Briarknoll pedestrian bridge; surveyed channel
END DESCRIPTION:
XS GIS Cut Line= 5
     3043269.381    13833591.595     3043378.053    13826802.523
     3043379.732    13826633.019     3043416.514    13826155.556
     3043305.655     13825973.49
#Sta/Elev= 30
       0   81.51    44.1   79.46  189.21   82.32  307.33   79.01   794.2   80.66
  1604.3   77.54 1857.72    80.8 2344.98   78.95  2414.4   76.59 2728.89   79.21
 3284.52   75.83 3614.56   78.42 4244.64   76.02 4334.65   78.89 4469.67   75.05
 4677.94   78.32 4884.66   75.79  5726.3   78.69 5829.66   76.36 5924.85   79.08
 6095.44   76.34 6434.92   78.98  6582.7   78.66 6641.77   75.62 6789.94   76.99
 6885.97   63.21 6887.71    65.7 6927.27   76.62 7411.31   78.48 7651.49   75.91
#Mann= 3 , 0 , 0
       0     .15       0 6789.94     .04       0 6927.27     .15       0
#XS Ineff= 2 , 0
       0    6780            6966       0
Permanent Ineff=
       T       T
Bank Sta=6789.94,6927.27
XS Rating Curve= 0
Exp/Cntr=.5,.3

Type RM Length L Ch R = 3 ,2618    ,,,
BEGIN DESCRIPTION:
Pedestrian Bridge at S. Briarknoll (?)
END DESCRIPTION:
Bridge Culvert--1,0,-1,-1, 0
Deck Dist Width WeirC Skew NumUp NumDn MinLoCord MaxHiCord MaxSubmerge Is_Ogee
31,5,2.6,0, 7, 7, , , .95, 0, 0,0,,
 6704.25 6815.36 6815.36 6860.36 6915.15 6915.15 6974.32
   76.59   78.01   78.01   77.78    77.8    77.8   77.32
             -.4   75.97   75.66    75.7
 6704.25 6815.36 6815.36 6860.36 6915.15 6915.15 6974.32
   76.59   78.01   78.01   77.78    77.8    77.8   77.32
             -.4   75.97   75.66    75.7
Pier Skew, UpSta & Num, DnSta & Num=  ,6851.54, 2 ,6851.54, 2 , 0 , 0 , 0 ,,
       1       1
       0     100
       1       1
       0     100
Pier Skew, UpSta & Num, DnSta & Num=  ,6888.96, 2 ,6888.96, 2 , 0 , 0 , 0 ,,
       1       1
       0     100
       1       1
       0     100
BR Coef=-1 , 1 , 1 ,1.25, 0 ,,,.8,-1,2,0,
WSPro=,,,, 1 ,,,, 0 ,,,, 0 ,,,,-1 ,-1 ,-1 , 0 , 0 , 0 , 0 , 0
BC Design=,, 0 ,, 0 ,,,,,,

Type RM Length L Ch R = 1 ,2615    ,102.58,100.16,100.04
BEGIN DESCRIPTION:
2615.184--d/s face S Briarknoll pedestrian bridge; channel copied from 2652
END DESCRIPTION:
XS GIS Cut Line= 6
     3043307.699    13833595.896     3043415.866     13826806.24
     3043415.833     13826668.85     3043415.865     13826636.99
     3043456.341    13826134.805      3043357.09    13825986.349
#Sta/Elev= 30
       0   81.53    48.4   79.52  183.42   82.05   303.4   78.92 1113.54   78.02
 1878.63   80.48 2370.73   78.87 2459.33   76.34 2853.76   78.93 3301.03   75.71
 3633.86   78.43  3978.9    75.6  4157.5   78.27  4246.1   75.97  4334.7   78.76
 4458.96   74.98 4668.99   78.26 4864.01   75.87 4909.02   78.45 5250.23   75.68
 5689.12    78.8 6091.93   75.75 6387.26   76.12 6484.22   78.75 6649.24   75.56
 6789.94   76.99 6885.97   63.21 6887.71    65.7 6927.27   76.62 7642.16   76.27
#Mann= 3 , 0 , 0
       0     .15       0 6789.94     .04       0 6927.27     .15       0
#XS Ineff= 2 , 0
       0    6780            6967       0
Permanent Ineff=
       T       T
Bank Sta=6789.94,6927.27
XS Rating Curve= 0
Exp/Cntr=.5,.3

Type RM Length L Ch R = 1 ,2515    ,2385.38,1339.62,709.54
BEGIN DESCRIPTION:
2515.024--d/s exit S Briarknoll pedestrian bridge; channel copied from 2652
END DESCRIPTION:
XS GIS Cut Line= 6
     3043422.003    13833600.775     3043515.866       13826807.
     3043515.861     13826641.06     3043554.034    13826167.457
     3043493.608    13826097.731     3043408.525    13826001.351
#Sta/Elev= 30
       0   81.46   68.28    79.5  240.47    81.7  323.31   79.06  473.32   82.25
 1054.31   79.03  2363.5   78.77  2378.5   80.92 3233.58   77.45 3278.59   75.16
 3421.83   77.77 3533.61   75.16 3623.62   78.09 3743.63   75.08 3848.64   77.75
 4176.47   77.84 4250.46   74.98 4324.44   78.34 4718.73   75.64 5003.75   78.79
  5508.2   76.11 5918.84   79.29 6098.86   76.12 6188.84   78.93 6558.79   78.34
 6647.57   75.56 6773.92   77.92 6880.97   63.21 6922.27   76.62 7656.33   76.56
#Mann= 3 , 0 , 0
       0     .15       0 6773.92     .04       0 6922.27     .15       0
#XS Ineff= 2 , 0
       0    6770            6964       0
Permanent Ineff=
       T       T
Bank Sta=6773.92,6922.27
XS Rating Curve= 0
Exp/Cntr=.3,.1

Type RM Length L Ch R = 1 ,1175    ,696.95,708.55,437.32
BEGIN DESCRIPTION:
 1175.405--surveyed channel
END DESCRIPTION:
XS GIS Cut Line= 5
     3045497.317    13826969.784       3044769.6    13826515.305
     3044603.106    13826514.112     3044260.959    13826185.643
     3043573.544     13826007.78
#Sta/Elev= 30
       0   76.14   70.39   76.89  153.05   74.36  188.42   76.17  259.16   77.39
  418.33   75.68  489.07   77.66  595.18   77.97  648.23   77.58  693.37   75.74
  825.08   78.28  885.04   75.89   923.1   64.78  925.26   62.63  932.74    62.1
  940.85   62.22  942.42   64.58  987.37    75.5 1024.47    77.8  1066.9   77.98
 1129.28    77.9 1191.66   75.21 1233.25   77.38 1265.06   77.81 1351.69   75.82
 1459.99      76 1499.21   78.44 2091.11      78 2153.09    79.5 2208.82   79.31
#Mann= 3 , 0 , 0
       0     .15       0  885.04     .04       0  987.37     .15       0
#XS Ineff= 2 , 0
       0     872            1019       0
Permanent Ineff=
       T       T
Bank Sta=885.04,987.37
XS Rating Curve= 0
Exp/Cntr=.3,.1

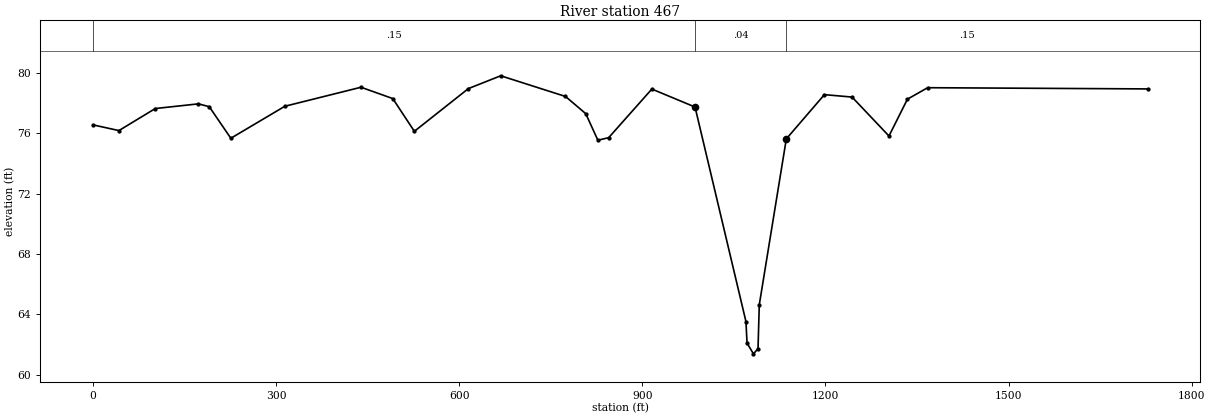
Type RM Length L Ch R = 1 ,467     ,121.08,466.86,54.9
BEGIN DESCRIPTION:
 466.856--surveyed channel
END DESCRIPTION:
XS GIS Cut Line= 4
     3045649.276    13826340.135     3044806.796    13825814.137
     3044634.308    13825799.217     3044077.174    13825730.576
#Sta/Elev= 30
       0   76.56   42.74   76.18   102.3   77.64  173.03   77.95  190.72   77.76
  226.08   75.67   314.5   77.79  439.27   79.05  491.34    78.3   526.7   76.13
  615.12   78.96  668.17   79.81  774.27   78.44  807.47    77.3  827.32   75.54
  845.01   75.71  915.74   78.93  986.48   77.74 1069.87   63.53 1071.68    62.1
 1082.15   61.39 1089.66   61.73 1091.71   64.64 1136.03   75.63 1198.38   78.56
 1243.72    78.4 1304.17   75.82  1334.4   78.26 1367.54   79.02 1727.68   78.94
#Mann= 3 , 0 , 0
       0     .15       0  986.48     .04       0 1136.03     .15       0
#XS Ineff= 2 , 0
       0     977            1140       0
Permanent Ineff=
       T       T
Bank Sta=986.48,1136.03
XS Rating Curve= 0
Exp/Cntr=.3,.1

Chan Stop Cuts=-1